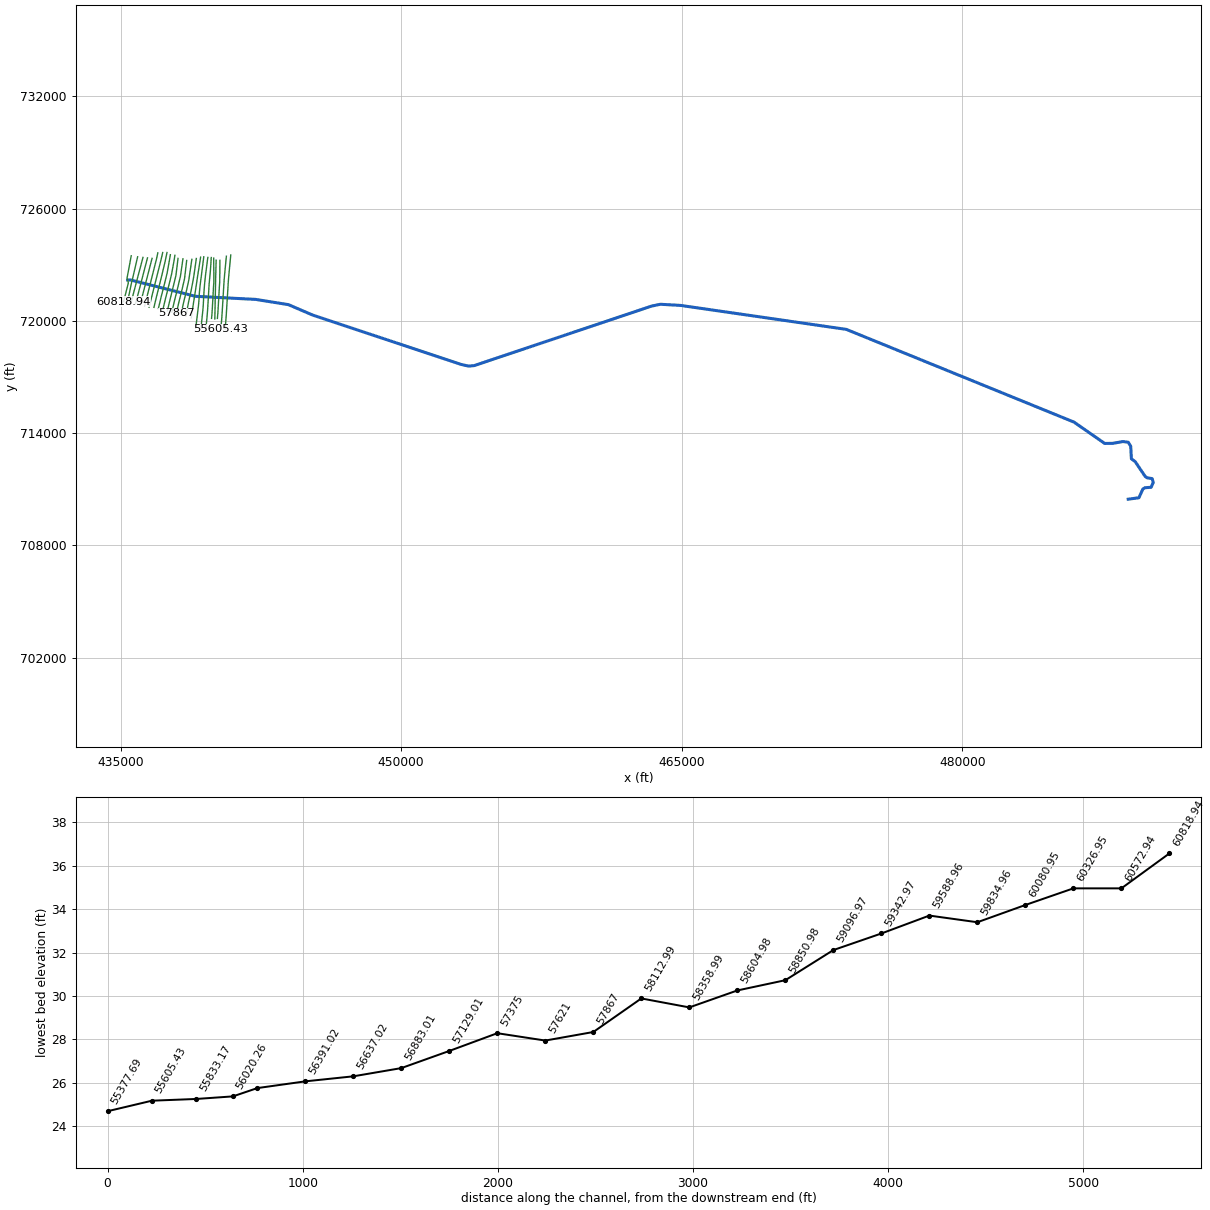
--- 691_ras.prj (project) ---

Proj Title=691
Current Plan=p01
Default Exp/Contr=0.3,0.1
English Units
Geom File=g01
Flow File=f01
Plan File=p01
Y Axis Title=Elevation
X Axis Title(PF)=Main Channel Distance
X Axis Title(XS)=Station
BEGIN DESCRIPTION:
RFD model 691 exported to HEC-RAS
END DESCRIPTION:

--- 691_ras.p01 (plan) ---

Plan Title=Plan 01
Program Version=4.10
Short Identifier=Plan 01
Geom File=g01
Flow File=f01
Subcritical Flow
Calc Critical at every XS
Secant Critical Depth

--- 691_ras.f01 (steady flow) ---

Flow Title=Flow 01
Program Version=5.01
Number of Profiles= 6
Profile Names=10yr,25yr,50yr,100yr,100plus,500yr
River Rch & RM=691,102,60818.94
    68.2  133.28  204.86  285.84  417.33 1014.79
River Rch & RM=691,102,59588.96
    69.7  136.24  209.46  292.31  426.77 1034.81
River Rch & RM=691,102,59342.97
   71.19  139.19  214.04  298.75  436.17 1054.68
River Rch & RM=691,102,59096.97
  624.56 1213.28  1861.3 2583.38 3771.73 6624.05
River Rch & RM=691,102,58850.98
  625.99  1216.2 1865.93    2590  3781.4 6639.68
River Rch & RM=691,102,58604.98
  626.98 1218.22 1869.14 2594.58 3788.09 6650.49
River Rch & RM=691,102,58358.99
  628.08 1220.47 1872.71 2599.67 3795.52 6662.49
River Rch & RM=691,102,58112.99
  629.18 1222.72 1876.27 2604.76 3802.95 6674.48
River Rch & RM=691,102,   57867
  630.38 1225.18 1880.19 2610.35 3811.12 6687.67
River Rch & RM=691,102,   57621
  631.04 1226.53 1882.32  2613.4 3815.57 6694.85
River Rch & RM=691,102,   57375
  642.72 1250.45 1920.28 2667.62 3894.73 6822.51
River Rch & RM=691,102,57129.01
  670.48 1307.28 2010.46 2796.43 4082.79 7124.22
River Rch & RM=691,102,56883.01
  973.52 1928.38 2997.43 4207.71 6143.2610324.22
River Rch & RM=691,102,56637.02
  975.45 1932.36 3003.76  4216.8 6156.5310344.42
River Rch & RM=691,102,56391.02
  978.73 1939.11 3014.53 4232.25 6179.0810378.71
River Rch & RM=691,102,56145.03
  981.23 1944.26 3022.76 4244.04  6196.310404.91
River Rch & RM=691,102,56020.26
   984.6 1951.26 3033.97 4260.21  6219.910441.14
River Rch & RM=691,102,55833.17
  985.61 1953.38 3037.38 4265.12 6227.08 10452.2
River Rch & RM=691,102,55605.43
  989.96 1962.44 3051.93 4286.11 6257.7210499.41
River Rch & RM=691,102,55377.69
  990.98 1964.56 3055.33 4291.02 6264.8910510.45
River Rch & RM=691,102,55149.95
   995.7 1974.39 3071.11 4313.78 6298.1310561.56
River Rch & RM=691,102,54922.22
   999.4 1982.09 3083.47 4331.62 6324.1710601.58
River Rch & RM=691,102,54694.48
 1002.81  1989.2 3094.89 4348.09 6348.2210638.54
River Rch & RM=691,102,   54239
 1005.59 1995.04 3104.32 4361.76 6368.1610669.47
River Rch & RM=691,102,53939.11
 2050.91 3988.68 6130.09 8506.2712419.1618396.89
River Rch & RM=691,102,53440.61
 2055.32 3998.11 6145.45 8528.6512451.8218443.56
River Rch & RM=691,102,53191.35
 2057.83 4003.47 6154.18 8541.3812470.41 18470.1
River Rch & RM=691,102, 52942.1
 2058.38 4004.63 6156.06  8544.112474.3818475.73
River Rch & RM=691,102,52692.85
    2059 4005.94 6158.19  8547.212478.9118482.16
River Rch & RM=691,102, 52443.6
 2063.79 4016.13 6174.73 8571.2312513.9918531.96
River Rch & RM=691,102,52194.34
 2064.25 4017.11 6176.33 8573.5512517.3918536.78
River Rch & RM=691,102,51945.09
 3343.79 6485.44 9953.8713784.4820125.3427706.29
River Rch & RM=691,102,51695.84
 3345.06 6488.18 9958.3813791.0820134.9827719.32
River Rch & RM=691,102,51446.58
 3346.79 6491.93 9964.5413800.1120148.1727737.14
River Rch & RM=691,102,51197.33
 3659.47 7170.77 11080.515438.0922539.6130951.93
River Rch & RM=691,102,50948.08
 3660.75 7173.5511085.0715444.8122549.4230965.05
River Rch & RM=691,102,50698.82
 3663.53 7179.5711094.9515459.3122570.5930993.27
River Rch & RM=691,102,50449.57
 3664.64 7182.0211099.01 15465.322579.3431005.07
River Rch & RM=691,102,50200.32
 3665.97 7184.9211103.7915472.33 22589.631018.85
River Rch & RM=691,102,49951.07
 3669.99  7193.711118.29 15493.7 22620.8 31060.8
River Rch & RM=691,102,49701.81
 3672.01 7198.1611125.6815504.6322636.7631082.43
River Rch & RM=691,102,49452.56
 3675.29 7205.4111137.7315522.4722662.81 31117.8
River Rch & RM=691,102,49203.31
 3678.05 7211.5311147.9215537.5922684.8831147.93
River Rch & RM=691,102,48954.05
 3679.78 7215.3811154.3415547.1222698.7931166.91
River Rch & RM=691,102, 48704.8
 3682.57  7221.611164.7115562.5222721.2831197.67
River Rch & RM=691,102,48455.55
  3683.7 7224.1211168.9115568.7522730.38 31210.1
River Rch & RM=691,102, 48206.3
 3685.05 7227.1311173.9515576.2522741.3331225.14
River Rch & RM=691,102,47957.04
 4293.42 8451.1313099.4218298.2626715.4636017.31
River Rch & RM=691,102,47707.79
 4294.65  8453.913104.0618305.1726725.5536030.91
River Rch & RM=691,102,47458.54
 4296.83  8458.813112.2718317.4226743.4336055.03
River Rch & RM=691,102,47209.28
 4299.35 8464.4513121.7418331.5526764.0636082.84
River Rch & RM=691,102,46960.03
 4301.27  8468.813129.0618342.4826780.0336104.46
River Rch & RM=691,102,46710.78
 4304.47 8476.0613141.2918360.82 26806.836140.91
River Rch & RM=691,102,46212.27
 4309.39 8487.2313160.1418389.0826848.0536197.09
River Rch & RM=691,102, 46147.3
 4310.31 8489.3213163.6618394.3626855.7636207.58
River Rch & RM=691,102,45656.26
 4314.26 8498.2913178.7918417.0326888.8636252.62
River Rch & RM=691,102,45165.22
 4317.65 8506.0513191.9318436.78 26917.736292.09
River Rch & RM=691,102,44183.14
 4322.38  8516.913210.3218464.4626958.1136347.56
River Rch & RM=691,102,43201.06
 4507.98 8928.7813896.6919483.6528446.1338324.97
River Rch & RM=691,102,42218.97
 4514.06 8942.5813919.9419518.5128497.0338393.75
River Rch & RM=691,102,41236.89
  4516.1 8947.2413927.8319530.3728514.3338417.27
River Rch & RM=691,102,40254.81
 4569.05 9069.4714135.9219844.73 28973.339046.52
River Rch & RM=691,102,40081.32
 4942.55 9930.3415601.6522060.55 32208.443452.64
River Rch & RM=691,102,39093.27
 4951.16 9950.1715635.4222111.64   32283 43553.7
River Rch & RM=691,102,37117.18
  4960.6 9972.2215673.2722169.24 32367.1   43669
River Rch & RM=691,102,35141.09
 4964.13 9980.5515687.6122191.1532399.0843713.14
River Rch & RM=691,102,   33165
 4967.78 9989.2815702.7922214.4732433.13 43760.7
River Rch & RM=691,102,32176.96
 6342.3412836.0720267.6928778.3542016.3955093.13
River Rch & RM=691,102,31188.91
 6344.0812840.2420274.9328789.4942032.6655115.11
River Rch & RM=691,102,30200.87
 6345.5612843.7820281.1128799.0142046.5655133.95
River Rch & RM=691,102,29212.82
  6913.914047.1322237.7931647.0146204.6360073.67
River Rch & RM=691,102,28224.78
 6915.25 14050.422243.4931655.7946217.4660090.87
River Rch & RM=691,102,27236.73
 6916.7514054.0222249.8331665.5846231.7560110.09
River Rch & RM=691,102,26248.69
 6918.0114057.0622255.15 31673.846243.7660126.27
River Rch & RM=691,102,26151.76
 6918.3214057.8222256.4831675.8646246.7660130.32
River Rch & RM=691,102,25227.84
 6919.5714060.8422261.7831684.0646258.73 60146.5
River Rch & RM=691,102,24303.92
 6920.7214063.6622266.7331691.7446269.9460161.66
River Rch & RM=691,102,23379.99
 8080.7316536.1126304.7537591.6654883.8370286.41
River Rch & RM=691,102,22456.07
 8088.7816555.3526338.2537643.2754959.1870384.84
River Rch & RM=691,102,21532.15
 8502.6617488.4627913.72 40011.558416.79 74652.5
River Rch & RM=691,102,20608.23
 8505.5217495.2927925.6340029.86 58443.674687.33
River Rch & RM=691,102,19684.31
 8506.5617497.7727929.9440036.51 58453.374699.88
River Rch & RM=691,102,19650.72
 8506.6817498.0427930.4240037.2558454.3974701.27
River Rch & RM=691,102, 17729.5
 8544.8217586.6928082.6540269.2958793.17 75130.3
River Rch & RM=691,102,16768.89
 8546.08 17589.728087.8840277.3758804.9675145.59
River Rch & RM=691,102,15808.29
 9451.2519526.6631261.0544926.1465592.1682932.52
River Rch & RM=691,102,14847.68
 9452.55 19529.731266.2844934.1665603.8882947.22
River Rch & RM=691,102,13887.07
 9453.6819532.3931270.9644941.3665614.3882960.59
River Rch & RM=691,102,12926.47
 9454.8619535.22 31275.944948.9865625.5182974.85
River Rch & RM=691,102,11965.86
 9455.9919537.9131280.5744956.1765636.0182988.22
River Rch & RM=691,102,11005.25
 9458.7819544.4931291.9944973.7365661.6583020.74
River Rch & RM=691,102,10044.64
 9459.8819547.1431296.6244980.8865672.0883034.11
River Rch & RM=691,102,9084.037
10407.1821585.37 34647.749905.61 72862.291215.91
River Rch & RM=691,102,8123.429
10408.3521588.1634652.5649913.0972873.1191229.65
River Rch & RM=691,102,7162.822
10409.4621590.82 34657.249920.2872883.6191242.96
River Rch & RM=691,102,6202.215
10463.2121718.28 34878.750261.2773381.4591867.13
River Rch & RM=691,102,5241.607
14952.4830386.46 48144.568483.9999986.63116345.8
River Rch & RM=691,102,    4281
14986.3630467.7648286.2968702.38100305.5116727.6
Boundary for River Rch & Prof#=691,102,1
Up Type= 0
Dn Type= 2
Boundary for River Rch & Prof#=691,102,2
Up Type= 0
Dn Type= 2
Boundary for River Rch & Prof#=691,102,2
Up Type= 0
Dn Type= 2
Boundary for River Rch & Prof#=691,102,2
Up Type= 0
Dn Type= 2
Boundary for River Rch & Prof#=691,102,2
Up Type= 0
Dn Type= 2
Boundary for River Rch & Prof#=691,102,2
Up Type= 0
Dn Type= 2

--- 691_ras.g01 (geometry) ---

Geom Title=691
Program Version=4.10

River Reach=691,102
Reach XY= 30
435382.097601622722191.884862644435538.185513946722192.333561028
438995.571134628721320.850446468442220.176652103721154.498682639
443977.592026055720873.037885982445278.084405304720314.086643664
453198.378143458717680.522137092453606.400736242717586.620725221
453903.748282338717614.701214551463387.631659747720796.810950592
463860.722639558720893.607059018464933.949491056720833.109491255
473796.654677631719551.430834751485965.323940066714595.810257307
487607.227928519713454.826129713488042.810416216713459.665935149
488577.151567278713555.742141018488864.575736609713518.571910402
488998.204186495 713309.22999778489035.618622156712632.765692775
  489241.8666088712478.649162778489767.514166981 711695.73101338
489878.303232995711616.722728794490142.125238567711575.949264603
490205.205417123711372.007583699490089.248728906711110.226261624
 489759.84885499711086.741864485 489648.84926346711017.685490413
489438.398491581710552.065970207488865.082569805710474.491383569

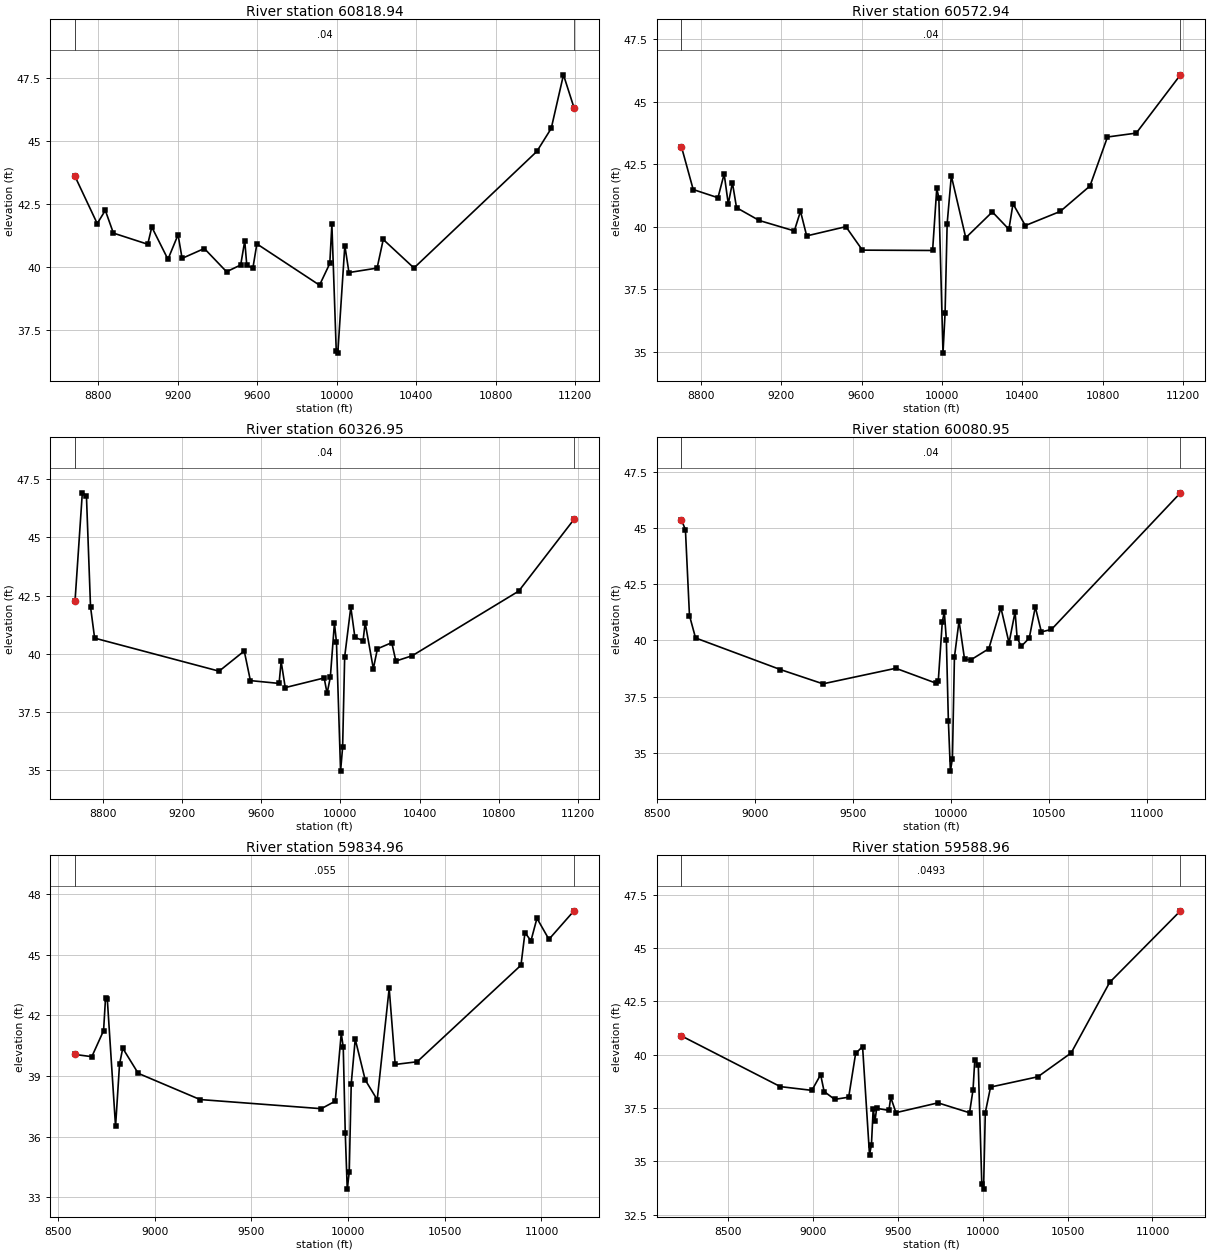
Type RM Length L Ch R = 1 ,60818.94,245.995400,245.995400,245.995400
XS GIS Cut Line= 6
435573.305767715723484.992153391435351.424252987722301.585901186
 435361.95265469722248.403630048435404.783213764722130.017409131
 435415.70004952722022.494883031435167.055767745721033.603264496
#Sta/Elev= 30
 8681.7843.580588793.68941.708388834.38642.231798875.08341.330239048.04540.88823
9068.39441.570759149.78840.292129200.65941.263889221.008 40.32789332.92540.71886
9444.84139.797319516.06140.06653 9536.4141.021479546.58440.067039577.10739.92881
9597.45540.90244 9912.9139.265429964.59840.125139975.09941.673279997.05836.66357
10004.8236.5696710040.2840.8365710061.0439.7659210202.7439.9426510233.6741.07679
10388.3439.9461111007.0244.5697511079.4645.4830511141.0647.6074711194.0646.30287
#Mann= 3 , 0 , 0
 8681.78    0.04       0 8681.78    0.04       011194.06    0.04       0
#XS Ineff= 2 , 0
       0 9710.15         10050.2       0
Bank Sta=8681.78,11194.06
Exp/Cntr=0.3,0.1

Type RM Length L Ch R = 1 ,60572.94,245.995300,245.995300,245.995300
XS GIS Cut Line= 6
435915.767018586723431.897733361435640.689169794722247.163517982
435620.521403581722171.017622173 435619.99741894722169.087482274
435600.147310406722092.651254326 435372.32323278721009.662556177
#Sta/Elev= 30
8703.97943.19707 8762.3941.489428885.58241.16252 8916.3842.112358936.91340.91392
8957.44541.762978977.97740.765239090.90340.253759265.42539.837439296.22340.62104
9327.02139.638249522.07540.006939604.20339.069749953.50139.056549974.191 41.5377
9984.53641.1588310005.2234.9580210015.5536.5631410025.8940.1252910046.5542.03515
10118.4539.5635710250.7140.5959410333.0439.9020910353.4840.9193210414.7940.05075
10588.5240.6155210736.4741.6310310823.55  43.58710966.6143.7420611186.6646.06884
#Mann= 3 , 0 , 0
8703.979    0.04       08703.979    0.04       011186.66    0.04       0
#XS Ineff= 2 , 0
       09772.846        10052.97       0
Bank Sta=8703.979,11186.66
Exp/Cntr=0.3,0.1

Type RM Length L Ch R = 1 ,60326.95,245.995400,245.995400,245.995400
XS GIS Cut Line= 6
436201.770427495723400.799323469435902.466667354722274.225883454
435857.924147695722106.568719357435857.400162995722104.638579428
435813.469385058 721936.82229504435559.070404909720965.014063879
#Sta/Elev= 30
8659.87242.244248696.91346.911098717.60746.791648738.301 42.01498758.99540.67052
 9387.2639.251349514.31940.117919545.35938.846179690.21638.725289700.56339.66935
9721.25738.546049917.84838.959939932.497  38.2979948.889 38.98969969.58241.31604
9979.92940.4890810000.63 34.958110010.9635.98395 10021.3 39.868610052.31 42.0007
10072.99 40.702810114.3340.5642910124.6741.3306110166.02 39.356910186.6940.21275
10259.0540.4759310279.7239.6856710362.4239.9144510899.9442.6900811179.0345.77097
#Mann= 3 , 0 , 0
8659.872    0.04       08659.872    0.04       011179.03    0.04       0
#XS Ineff= 2 , 0
       09776.727        10045.84       0
Bank Sta=8659.872,11179.03
Exp/Cntr=0.3,0.1

Type RM Length L Ch R = 1 ,60080.95,245.995400,245.995400,245.995400
XS GIS Cut Line= 6
436442.393960655723374.635267302436139.510988235722211.756016791
436095.786594182722043.881969079 436095.28084299722041.946971476
436051.827718914721874.002745464435801.635116933 720907.02042171
#Sta/Elev= 30
8623.84945.351688644.139 44.91348664.80641.104698695.80740.10812 9129.8238.70222
9346.826 38.07019718.83738.760919925.50938.096459935.84338.18415 9956.5140.82963
9966.84441.258729977.17740.038649987.51136.433749997.84534.1913910008.1834.75201
10018.5139.2609210042.0440.8643410070.1539.1658910101.1439.12884 10194.139.62902
10256.08 41.4453 10297.439.8878210328.3841.2678210338.7140.1224710359.3739.73101
10400.6940.1013910431.6841.4843510462.6640.3759610514.31 40.4876 11173.346.55623
#Mann= 3 , 0 , 0
8623.849    0.04       08623.849    0.04       0 11173.3    0.04       0
#XS Ineff= 2 , 0
       09782.234         10043.2       0
Bank Sta=8623.849,11173.3
Exp/Cntr=0.3,0.1

Type RM Length L Ch R = 1 ,59834.96,245.995400,245.995400,245.995400
XS GIS Cut Line= 6
436686.763761073723348.063862979436377.175912023722149.636672184
 436333.78682366721981.675741509436333.281072468721979.740743905
436290.025285482721811.745572552436042.261535941720849.490196789
#Sta/Elev= 30
8587.75640.06245 8674.7739.953158735.51741.239818745.84542.880568754.73342.81598
8797.48636.499828818.14339.588258834.69540.371088914.65739.129019234.50737.83103
9861.29937.378449933.59737.751389964.58241.11515 9974.9140.414049985.238 36.1957
9995.56733.39596 10005.934.2418210016.2238.6172610036.8740.81986 10088.538.80364
10150.4637.8228510212.4243.33869 10243.439.5683810356.9939.7011510893.9544.48114
 10914.646.0943810945.5845.6898310976.5646.8046311038.5145.7629711168.1247.17366
#Mann= 3 , 0 , 0
8587.756   0.055       08587.756   0.055       011168.12   0.055       0
#XS Ineff= 2 , 0
       09790.777        10041.18       0
Bank Sta=8587.756,11168.12
Exp/Cntr=0.3,0.1

Type RM Length L Ch R = 1 ,59588.96,245.995300,245.995300,245.995300
XS GIS Cut Line= 6
436994.695538968723642.077123851436917.509121329723288.953554645
436572.231160074721921.231918231436571.741642714 721919.29275015
436528.544649065721747.886277378436287.367049724720790.889086425
#Sta/Elev= 30
8226.90840.879878809.03538.504838994.68238.329399046.25139.064069066.87838.27606
9128.76137.907239211.44438.010379252.29940.059449293.15440.382259334.009 35.3101
9345.34935.776569355.66337.456469365.976 36.8983 9376.2937.486889448.48637.39136
  9458.838.008739489.741 37.28559737.27137.744519922.91837.280349943.54538.35923
9953.85939.765569974.48639.498039995.11433.9361910005.4333.7031510015.7437.28918
10046.6838.4842910325.1238.9657710521.0640.0818910747.9443.3897611164.6946.73989
#Mann= 3 , 0 , 0
8226.908  0.0493       08226.908  0.0493       011164.69  0.0493       0
#XS Ineff= 2 , 0
       09802.893           10041       0
Bank Sta=8226.908,11164.69
Exp/Cntr=0.3,0.1

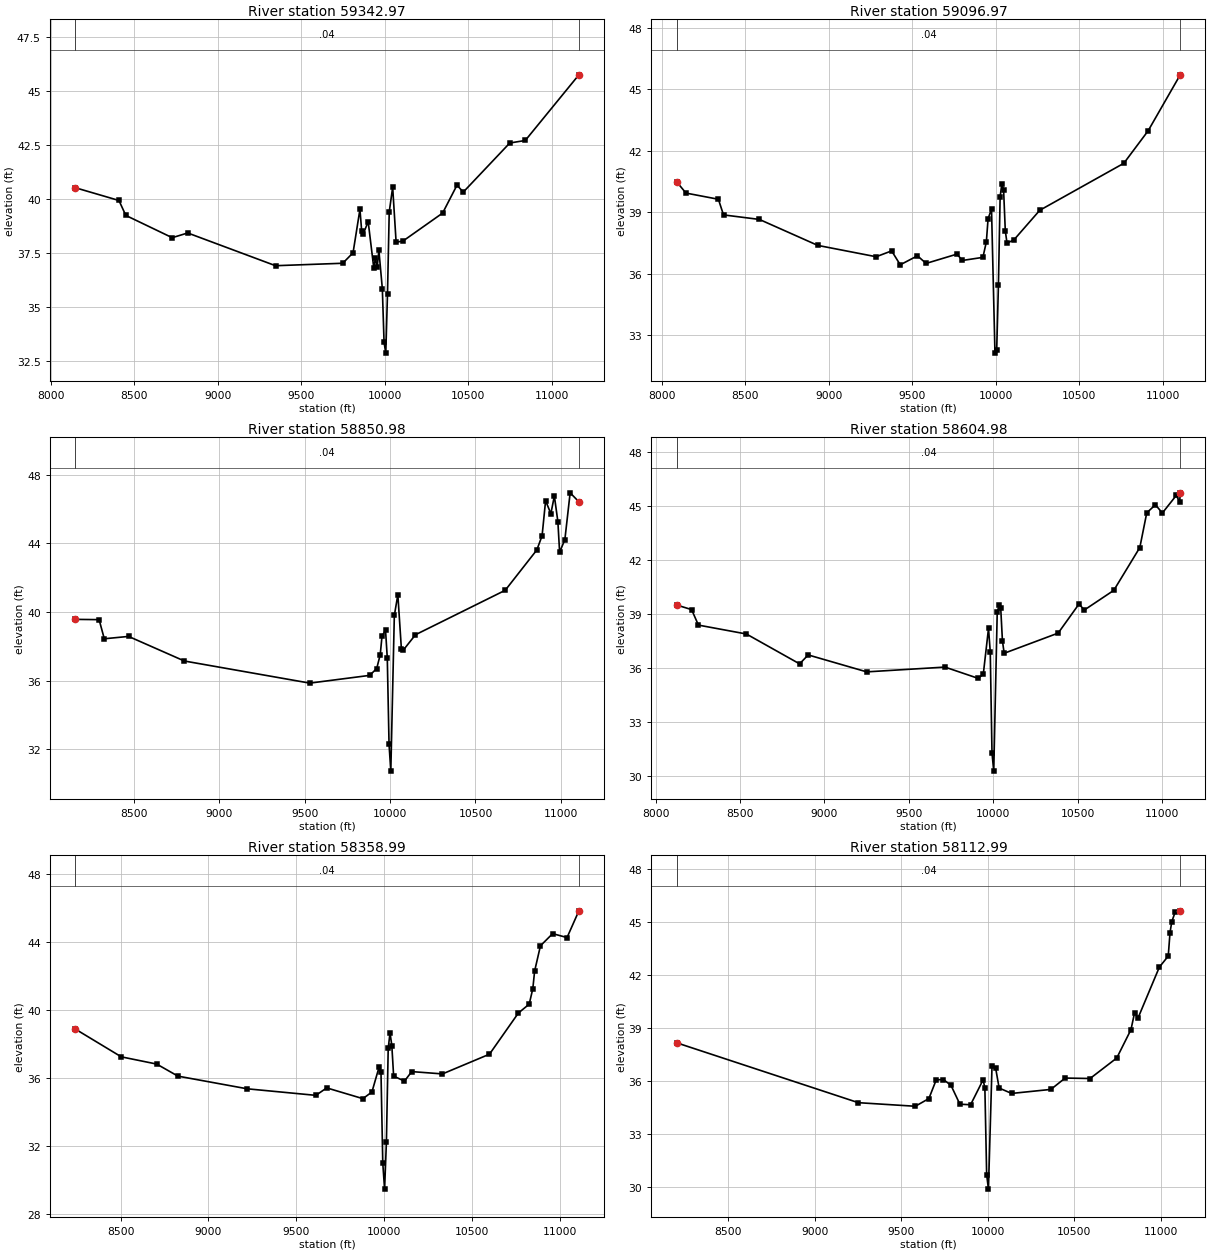
Type RM Length L Ch R = 1 ,59342.97,245.995400,245.995400,245.995400
XS GIS Cut Line= 6
437255.999100685723660.098059118437161.416267842723251.237891495
436854.776559293722035.585192546436810.744345725721861.022415191
436810.254828364 721859.08324714436526.585031003720733.695598185
#Sta/Elev= 30
8145.58240.518428407.416 39.92828448.47339.238578726.37138.20975 8819.1938.42764
9345.16536.91531 9747.3837.02866 9809.2637.512419850.51339.521519860.82638.52178
9871.13938.401519899.828 38.95049933.01836.831839943.33237.252949953.645 36.8417
9963.95837.622719984.58535.855339994.89833.3815710005.2132.8773610015.5235.62744
10025.8439.3906410046.4640.5429110067.0938.0008610108.3438.0553310345.53 39.3465
10431.6340.6350110469.2940.3159610747.73 42.583610840.5542.7003211161.5945.73258
#Mann= 3 , 0 , 0
8145.582    0.04       08145.582    0.04       011161.59    0.04       0
#XS Ineff= 2 , 0
       09805.935        10041.04       0
Bank Sta=8145.582,11161.59
Exp/Cntr=0.3,0.1

Type RM Length L Ch R = 1 ,59096.97,245.995400,245.995400,245.995400
XS GIS Cut Line= 6
437484.264280945723660.098059118437388.903695107723198.809920147
437204.884595186722424.564267799436919.612437129721283.509945527
436843.728314668 720968.14725399436788.323085755720727.743349254
#Sta/Elev= 30
8089.272 40.48868145.53539.931898339.55239.629978370.18738.865778584.78738.64485
8934.25837.375889283.72936.821619376.29137.107689427.82436.427799530.88936.86747
9582.422 36.4952 9767.9436.95172 9798.8636.638999922.539 36.79139943.15237.55032
9953.45838.681389974.07139.149989994.68532.1127810004.9932.25978 10015.335.42911
10025.6139.7546310035.9240.3854710046.2340.0975310056.5438.0825510066.85 37.4858
10108.09 37.645810262.7239.0912310765.7441.3868310911.2142.9734711103.3745.70871
#Mann= 3 , 0 , 0
8089.272    0.04       08089.272    0.04       011103.37    0.04       0
#XS Ineff= 2 , 0
       0 9703.84        10041.07       0
Bank Sta=8089.272,11103.37
Exp/Cntr=0.3,0.1

Type RM Length L Ch R = 1 ,58850.98,245.995400,245.995400,245.995400
XS GIS Cut Line= 6
437664.473633826723542.961979762437622.015474111723287.738610476
437493.725810796722570.520927995 437355.18053475722004.203257322
437168.435844362721269.936735481437024.539478898720665.082876191
#Sta/Elev= 30
8156.00239.57165 8295.8639.555618326.273 38.44078468.30938.578148795.33737.14377
 9529.7435.855129880.36236.306139921.649 36.70369942.29337.515599952.61438.58476
9973.25838.94364 9983.5837.323329993.90132.2856110004.2230.7236710024.8639.79833
10045.4941.0106310066.12 37.859910076.4437.7679410148.6538.6754610674.3441.26813
 10859.443.6191210890.2144.4475110910.7446.4932510941.5545.7324610962.0846.76655
10982.6245.2752110992.8843.4842811023.6944.2280411054.4946.9499311105.7446.42775
#Mann= 3 , 0 , 0
8156.002    0.04       08156.002    0.04       011105.74    0.04       0
#XS Ineff= 2 , 0
       09544.676        10040.54       0
Bank Sta=8156.002,11105.74
Exp/Cntr=0.3,0.1

Type RM Length L Ch R = 1 ,58604.98,245.995300,245.995300,245.995300
XS GIS Cut Line= 6
437907.756260186 723512.92708762437865.053652734723242.182945579
437730.919814676722509.402032509437593.173940063721942.889471471
437407.108819157 721208.45116955  437263.5035353720601.840948105
#Sta/Elev= 30
8124.28739.479948213.30139.222618253.79638.361688537.84137.867758852.99136.20885
8903.822  36.7059250.65835.763739713.88336.029619909.93235.40621 9940.8935.62961
9971.84938.177329982.16936.884129992.48831.2670210002.8130.2505810023.4439.06835
10033.7539.4515510044.0639.3317910054.3837.4804210064.6936.7971310384.4237.91787
10508.1339.53718   1053939.1972210713.9240.2929210868.0542.6713710909.1144.59825
10960.4345.0453811001.4944.5875711083.6145.5609611104.1445.2203811107.3845.70925
#Mann= 3 , 0 , 0
8124.287    0.04       08124.287    0.04       011107.38    0.04       0
#XS Ineff= 2 , 0
       09377.464                       0
Bank Sta=8124.287,11107.38
Exp/Cntr=0.3,0.1

Type RM Length L Ch R = 1 ,58358.99,245.995400,245.995400,245.995400
XS GIS Cut Line= 6
438073.885249645723345.432600409437965.387320995722450.783533216
437916.936517417  722243.5814735437624.895357847721049.469796196
437562.489433467720785.648943514437506.566729248720539.238658667
#Sta/Elev= 30
8242.13138.883218504.47237.246668705.93736.822098826.81636.112529221.16335.36783
9612.00734.982759673.768 35.42159879.64134.788799931.10935.180539972.28336.66088
9982.57736.37628 9992.8730.9959510003.1629.4694910013.4632.2320310023.7637.73973
10034.0538.6612810044.3537.9129310054.6436.1116210116.4235.82038 10157.636.37952
10332.6336.24331 10600.337.4035510764.7239.8225410826.3740.3458910846.9241.25609
 10857.242.2899310890.3743.7762910959.7444.4902111041.7844.2603211109.2145.83176
#Mann= 3 , 0 , 0
8242.131    0.04       08242.131    0.04       011109.21    0.04       0
#XS Ineff= 2 , 0
       09247.303                       0
Bank Sta=8242.131,11109.21
Exp/Cntr=0.3,0.1

Type RM Length L Ch R = 1 ,58112.99,245.995400,245.995400,245.995400
XS GIS Cut Line= 6
438338.024167746723322.262519911438203.187594146722391.344373941
438075.727177262721850.408418134437875.316321939721041.727287889
437801.947666883720726.643287987 437746.85132274720477.384855926
#Sta/Elev= 30
8202.70338.176229252.44634.78145 9581.21 34.57859659.58435.013819702.09836.07583
9743.40936.09297 9787.12 35.76749838.653 34.69569900.49234.664479972.63836.07444
9982.94435.627389993.25130.7061510003.56 29.882910024.1636.8385310044.7636.76204
10065.3635.6104310137.4635.3054110364.06 35.533610446.4736.1768710590.48 36.1515
 10744.537.3127610826.6438.9235610847.1739.8707110867.6839.5875410990.5742.46522
11041.7843.0888711052.0244.4146911062.2645.0405611082.7545.6069711111.0345.65334
#Mann= 3 , 0 , 0
8202.703    0.04       08202.703    0.04       011111.03    0.04       0
#XS Ineff= 2 , 0
       09148.858                       0
Bank Sta=8202.703,11111.03
Exp/Cntr=0.3,0.1

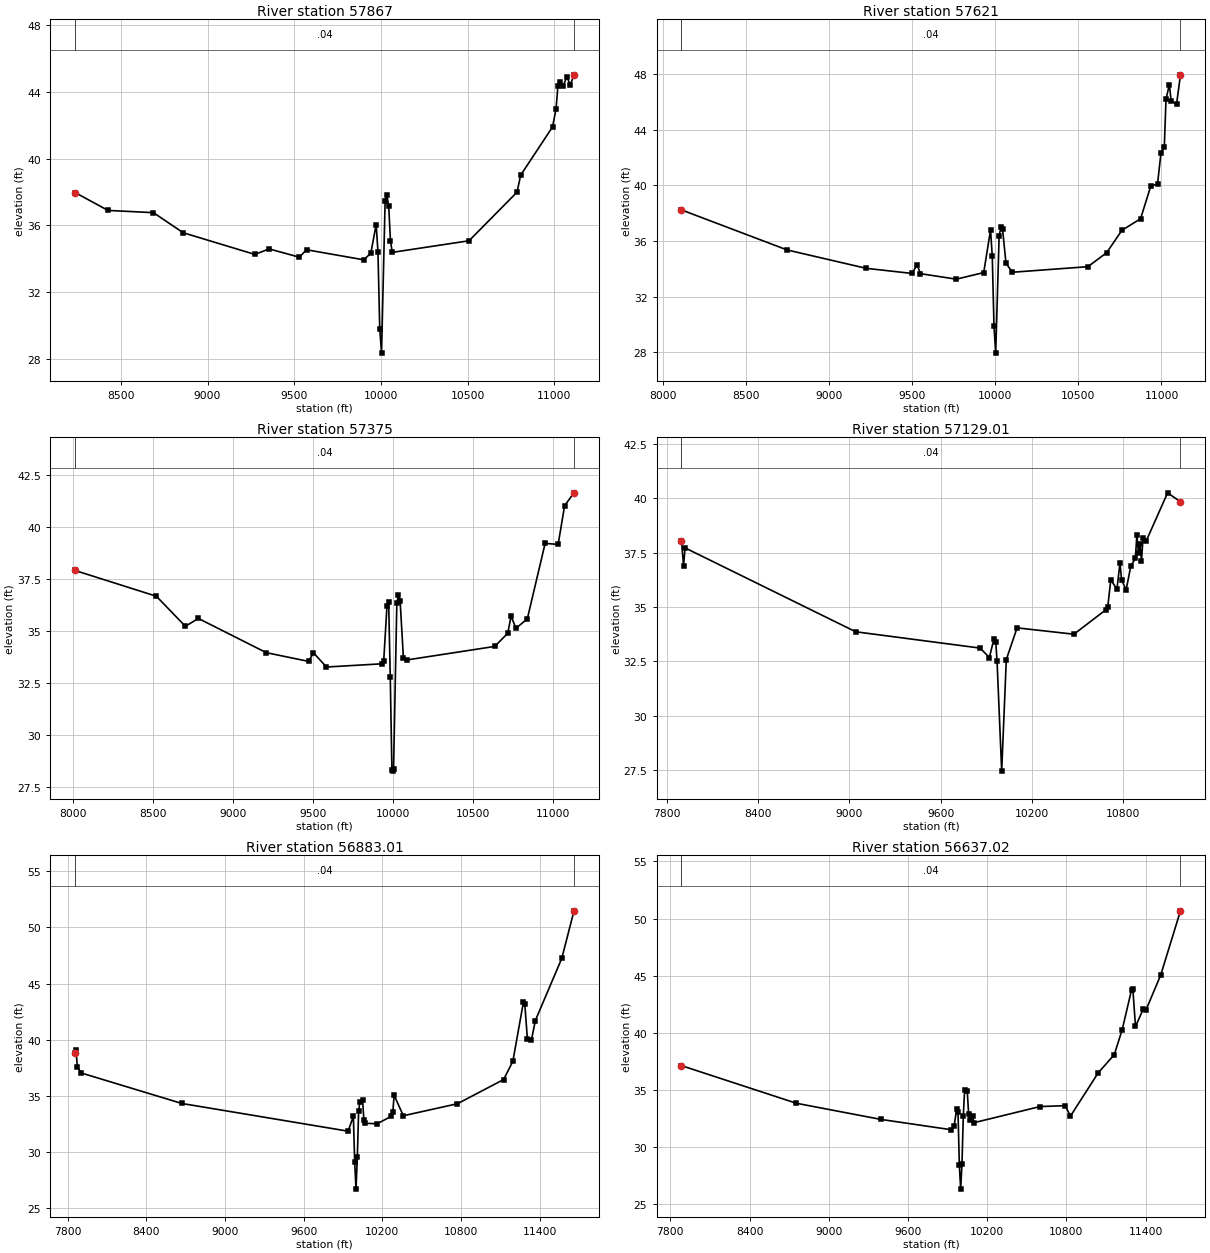
Type RM Length L Ch R = 1 ,   57867,245.995400,245.995400,245.995400
XS GIS Cut Line= 6
438537.286860347723234.216213867438421.983870089722255.865566999
438308.075318903721763.652381435438125.563123107721028.890863195
438060.514338732720743.584231809437990.238708466 720414.04940033
#Sta/Elev= 30
8236.00337.967958426.52936.893058688.32836.759198859.50535.555989273.25134.25343
9355.23234.586329529.64234.087439570.76434.534929900.25133.931649941.494 34.3225
9972.426 36.04729982.73634.404699993.04729.8031210003.3628.3348210023.9937.43462
 10034.337.7944310044.6137.1629610054.9235.0629710065.2434.3774710507.9635.07389
10784.8637.9925810805.3139.0037210989.3641.9011111009.8142.9999111020.0344.34002
11030.2644.5957511050.7144.3296811071.1644.9243311091.61  44.41311113.0345.02561
#Mann= 3 , 0 , 0
8236.003    0.04       08236.003    0.04       011113.03    0.04       0
#XS Ineff= 2 , 0
       0 9056.41                       0
Bank Sta=8236.003,11113.03
Exp/Cntr=0.3,0.1

Type RM Length L Ch R = 1 ,   57621,245.995300,245.995300,245.995300
XS GIS Cut Line= 6
438812.889101028723294.019931152438652.601495147722196.969670072
438539.448332131721679.195642158438377.209474057721011.219510883
438306.761134684720683.793759108 438240.40407002720349.676359639
#Sta/Elev= 30
8112.43138.24081 8748.1335.360129223.14234.040479499.02933.671659529.73934.28816
9550.25833.653929765.76733.25939 9930.5733.73354 9971.7736.800479982.07134.89281
9992.37129.9058310002.6827.9408910023.2836.3422310033.59 36.990410043.8936.86878
 10064.534.4067610102.7533.7566710557.4334.1578310669.9535.1614810762.0136.77221
 10874.237.6062710935.3739.9485810976.1540.1088110996.5442.2992711016.9342.77833
11027.1346.2070211047.52 47.255611057.7146.1018111090.5245.8311611114.1247.95382
#Mann= 3 , 0 , 0
8112.431    0.04       08112.431    0.04       011114.12    0.04       0
#XS Ineff= 2 , 0
       08961.085                       0
Bank Sta=8112.431,11114.12
Exp/Cntr=0.3,0.1

Type RM Length L Ch R = 1 ,   57375,245.995400,245.995400,245.995400
XS GIS Cut Line= 6
439052.472434402723339.158820063438925.554544717722441.166544154
 438861.56155476722072.692841038438764.934004068721579.781140804
438633.187607795  720991.6617603 438499.81709528720267.252225757
#Sta/Elev= 30
8010.941 37.9245 8520.1136.685928701.89935.239398782.69435.619239208.30733.97333
9472.61733.553359503.13633.967559584.61333.283659932.46733.438359942.72933.57871
9963.252  36.2219973.51336.427429983.77432.821959994.03628.35501    999928.27953
 10004.328.3760710024.8336.36149 10035.136.7292410045.3636.4691110065.89 33.7323
10086.4233.6224110637.8934.2738110719.3234.9126810739.6335.73207 10770.1  35.145
 10841.235.5948310952.9439.22943 11034.239.1748611074.8341.0425811133.4841.65639
#Mann= 3 , 0 , 0
8010.941    0.04       08010.941    0.04       011133.48    0.04       0
#XS Ineff= 2 , 0
       08870.413                       0
Bank Sta=8010.941,11133.48
Exp/Cntr=0.3,0.1

Type RM Length L Ch R = 1 ,57129.01,245.995400,245.995400,245.995400
XS GIS Cut Line= 6
439281.639101028723408.603264526439128.190074623722437.503129959
438995.115099251721550.492600337438958.941068888721326.068071753
438907.458713323721002.266444191438781.576718539720161.255486101
#Sta/Elev= 30
7893.592 38.03757907.36436.900927917.48837.714889041.06333.861519860.27433.11261
9921.04732.678759951.43433.544929963.01633.398119971.69232.5006910002.0827.46154
10032.4632.5843610103.3434.0414810477.78 33.749810690.1234.8843410700.23 34.9854
10720.4536.2486710760.8935.8196610781.1237.0246210791.23 36.255510821.5635.78192
 10851.936.8685710882.2337.2353710892.3438.3248410902.45 37.472810912.57 37.8969
10922.6837.1235910932.7938.1891810953.0138.0229711094.5740.2437911179.2539.83181
#Mann= 3 , 0 , 0
7893.592    0.04       07893.592    0.04       011179.25    0.04       0
#XS Ineff= 2 , 0
       0                               0
Bank Sta=7893.592,11179.25
Exp/Cntr=0.3,0.1

Type RM Length L Ch R = 1 ,56883.01,245.995400,245.995400,245.995400
XS GIS Cut Line= 6
439451.777989924723432.908820063439246.595498294721834.778735846
439217.156725883721530.231740415439193.593929738721117.951327249
  439168.0645127720825.821507767439025.618565291719652.699607059
#Sta/Elev= 30
7856.43538.793457864.41239.080397874.49837.558587904.75637.022848671.28634.30682
9939.24731.835619979.29333.166589989.30529.054329999.31626.6706710009.3329.49439
10019.3433.6459210029.3534.4614510049.3734.6183510059.3832.8599910069.39 32.5422
10159.5532.4947510269.8733.16924 10279.933.5060610289.9335.0468310360.1933.21188
10772.4634.28284   1112536.4396111195.5738.0733811276.2343.3577711286.3243.21621
11306.4840.0183811336.73 39.950911366.9841.7026411568.6247.2457811661.6851.48139
#Mann= 3 , 0 , 0
7856.435    0.04       07856.435    0.04       011661.68    0.04       0
#XS Ineff= 2 , 0
       0                               0
Bank Sta=7856.435,11661.68
Exp/Cntr=0.3,0.1

Type RM Length L Ch R = 1 ,56637.02,245.995300,245.995300,245.995300
XS GIS Cut Line= 6
439667.055767715723398.186597824439541.933342487722430.144614831
439490.339998513721936.829860076439464.158716023721594.873557448
439415.809967667720713.356613427439303.802921295 719636.52476804
#Sta/Elev= 30
7884.02337.110578754.391 33.81469398.11232.392999929.24231.493969949.26631.78478
9969.28933.296579979.30133.066539989.31228.424899999.32426.2917610009.3328.49173
10019.34  32.70410029.35 34.955310049.3834.8903510059.3932.89562 10069.432.34079
10089.4232.7152710099.4332.1083810600.4233.5256610791.1333.6043510831.3232.69236
11042.3236.4941211163.0238.0666611223.3740.2644911293.7843.7342911303.8343.84602
11323.9540.5400411384.3242.1017911404.4542.0097911515.2145.05425 11664.7 50.6731
#Mann= 3 , 0 , 0
7884.023    0.04       07884.023    0.04       0 11664.7    0.04       0
#XS Ineff= 2 , 0
       0                               0
Bank Sta=7884.023,11664.7
Exp/Cntr=0.3,0.1

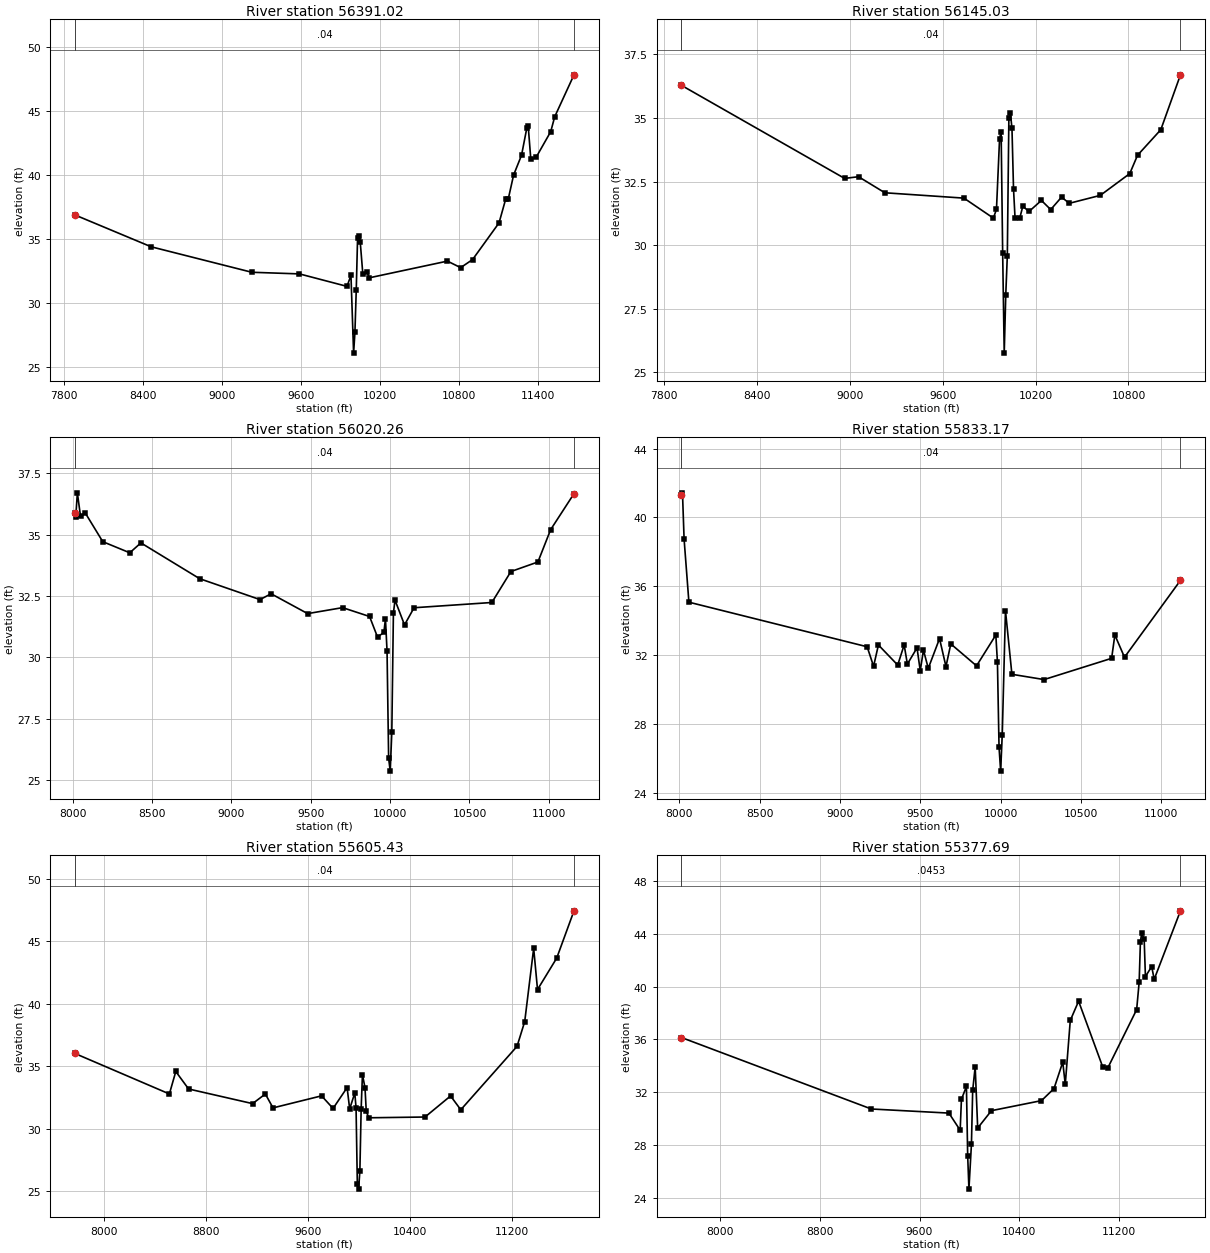
Type RM Length L Ch R = 1 ,56391.02,245.995400,245.995400,245.995400
XS GIS Cut Line= 6
439851.083545506723391.242153391439802.860665351 722658.44804205
439737.843293965721990.735157073439654.979151458720578.588921174
439619.139574021720151.419233635439564.765032738719619.525155067
#Sta/Elev= 30
7886.571 36.85518464.05934.369229227.33932.377579588.29232.250789948.81631.27577
9978.85532.141459998.88126.0596610008.8927.6719310018.9130.9723710028.9235.04125
10038.9335.2290210048.9434.7719110068.9732.21749   1009932.3980710119.0331.94788
10710.0733.2499910810.3932.7399710900.6733.3689111101.43 36.236911151.6438.08572
11171.7438.1183611211.9339.9767911272.2141.52727 11312.443.6645411322.4543.82092
11342.5441.1927211382.7441.3627411493.3643.3680411523.5244.5287111669.8247.80639
#Mann= 3 , 0 , 0
7886.571    0.04       07886.571    0.04       011669.82    0.04       0
#XS Ineff= 2 , 0
       0                               0
Bank Sta=7886.571,11669.82
Exp/Cntr=0.3,0.1

Type RM Length L Ch R = 1 ,56145.03,124.765700,124.765700,124.765700
XS GIS Cut Line= 6
439980.692524278723359.432525269439990.671229952722110.858484543
439968.725990974721787.238656647 439907.98006677720671.166800401
439888.864809417720401.027438662439867.173724019 720138.45133563
#Sta/Elev= 30
7910.95936.284958965.42532.623899055.42832.690229225.58232.058399736.57631.84791
9926.82531.06106 9946.8531.408489966.87634.188229976.88834.466519986.90129.67273
9996.91325.7487610006.9328.0529810016.9429.5791110026.95 34.983210036.9635.18117
10046.9834.5980110056.9932.21303   1006731.0488710097.0431.0555910117.0731.52831
10157.1231.3218310237.23 31.757210297.3131.3972310367.42 31.886710417.5131.64379
10617.88 31.956110808.3532.8138510858.48 33.534311008.9734.5409311135.9536.69944
#Mann= 3 , 0 , 0
7910.959    0.04       07910.959    0.04       011135.95    0.04       0
#XS Ineff= 2 , 0
       08326.491                       0
Bank Sta=7910.959,11135.95
Exp/Cntr=0.3,0.1

Type RM Length L Ch R = 1 ,56020.26,187.090500,187.090500,187.090500
XS GIS Cut Line= 5
440112.297030926 723249.90779072440084.720915645722237.592711031
440066.634669483721286.374764845440064.578459114721240.452731997
440041.622335225720107.749023587
#Sta/Elev= 30
8015.37235.900518020.28235.727618030.28636.703088050.29335.742898080.30435.88037
8190.34534.713328360.40834.260748430.43434.663838800.57133.205529180.68332.35434
9250.696 32.59139480.73831.783049700.77732.026519870.80831.665499920.81730.82741
9960.82431.016179970.82631.568149980.82930.251769990.83925.8868810000.8525.36683
10010.8626.9566810020.8731.7942210030.8732.3347910090.8931.32337 10150.932.02216
   1064132.2359210761.0233.4972710931.0633.8861511011.0835.2015211158.3636.66979
#Mann= 3 , 0 , 0
8015.372    0.04       08015.372    0.04       011158.36    0.04       0
#XS Ineff= 2 , 0
       08324.765        10756.92       0
Bank Sta=8015.372,11158.36
Exp/Cntr=0.3,0.1

Type RM Length L Ch R = 1 ,55833.17,227.738800,227.738800,227.738800
XS GIS Cut Line= 6
440314.025857627 723241.37696971440303.495359898722111.010039076
440285.587735921721840.367525637440218.987230659720671.401999071
440200.556500345720400.794726327440179.979003757720137.461584032
#Sta/Elev= 30
8012.91941.324658019.29641.429318029.29638.741928059.29835.071079169.402  32.479
9209.48931.344959239.55532.582949359.81731.415429399.90532.588299419.94531.47369
9480.04132.415119500.07331.088889520.10532.281619550.15331.226999620.26532.95355
9660.328 31.32759690.37632.644839850.63231.369969970.82433.16156 9980.84 31.5892
9990.85626.6453810000.8725.2482810010.8927.3761610030.92 34.579610070.99 30.8782
10271.3230.5715810692.08 31.806910712.13 33.163310772.2631.87042 11120.836.33882
#Mann= 3 , 0 , 0
8012.919    0.04       08012.919    0.04       0 11120.8    0.04       0
#XS Ineff= 2 , 0
       08281.243        10757.39       0
Bank Sta=8012.919,11120.8
Exp/Cntr=0.3,0.1

Type RM Length L Ch R = 1 ,55605.43,227.738900,227.738900,227.738900
XS GIS Cut Line= 6
440659.212290704 723461.75158307440565.083741248722494.251780897
440533.015156746722098.436932877440429.536565751720388.250083864
440400.484571636719992.201278925 440362.82485196719559.976782307
#Sta/Elev= 30
7774.15636.015238514.38732.779298564.62334.575338665.09533.177119166.82532.00666
9267.04532.774559327.17731.665499707.95232.628239798.09931.620469908.27833.28856
9928.31131.581479968.37632.857689978.39331.680269988.40925.590029998.42625.16804
10008.4426.6387810018.4631.6161110028.4734.31985 10048.533.2850810058.5231.38258
10078.5530.8735210519.2630.9348910719.6532.6201210799.8131.5151811240.9536.58802
11301.1638.5703911371.4244.4249111401.5441.1286111552.1143.6449511687.6447.42485
#Mann= 3 , 0 , 0
7774.156    0.04       07774.156    0.04       011687.64    0.04       0
#XS Ineff= 2 , 0
       08480.548        10758.32       0
Bank Sta=7774.156,11687.64
Exp/Cntr=0.3,0.1

Type RM Length L Ch R = 1 ,55377.69,227.738800,227.738800,227.738800
XS GIS Cut Line= 6
  440893.9425143723528.918363899440792.921554446722481.249735117
440761.143376768722085.494967788440656.224670708720375.390021175
440627.464189261719979.319779932440590.045200169 719545.44631733
#Sta/Elev= 30
7693.77936.142629213.98630.740589835.24530.430079925.40129.135099935.41831.46829
9975.48732.444819985.50427.211149995.522  24.68210015.56 28.070610025.5732.14801
10045.6133.9348310065.6429.2999310175.8230.61376 10576.531.37314 10676.732.28486
10746.8434.2848710766.8832.6000410806.9637.4325110873.5838.8908511067.6133.89956
11107.7233.8498811338.4138.2524911358.4940.3220511368.5243.3505211378.5644.05262
11398.6443.5629611408.6740.7537811458.86 41.509511478.9340.5452611689.2645.72238
#Mann= 3 , 0 , 0
7693.779  0.0453       07693.779  0.0453       011689.26  0.0453       0
#XS Ineff= 2 , 0
       08631.921         10758.8       0
Bank Sta=7693.779,11689.26
Exp/Cntr=0.3,0.1