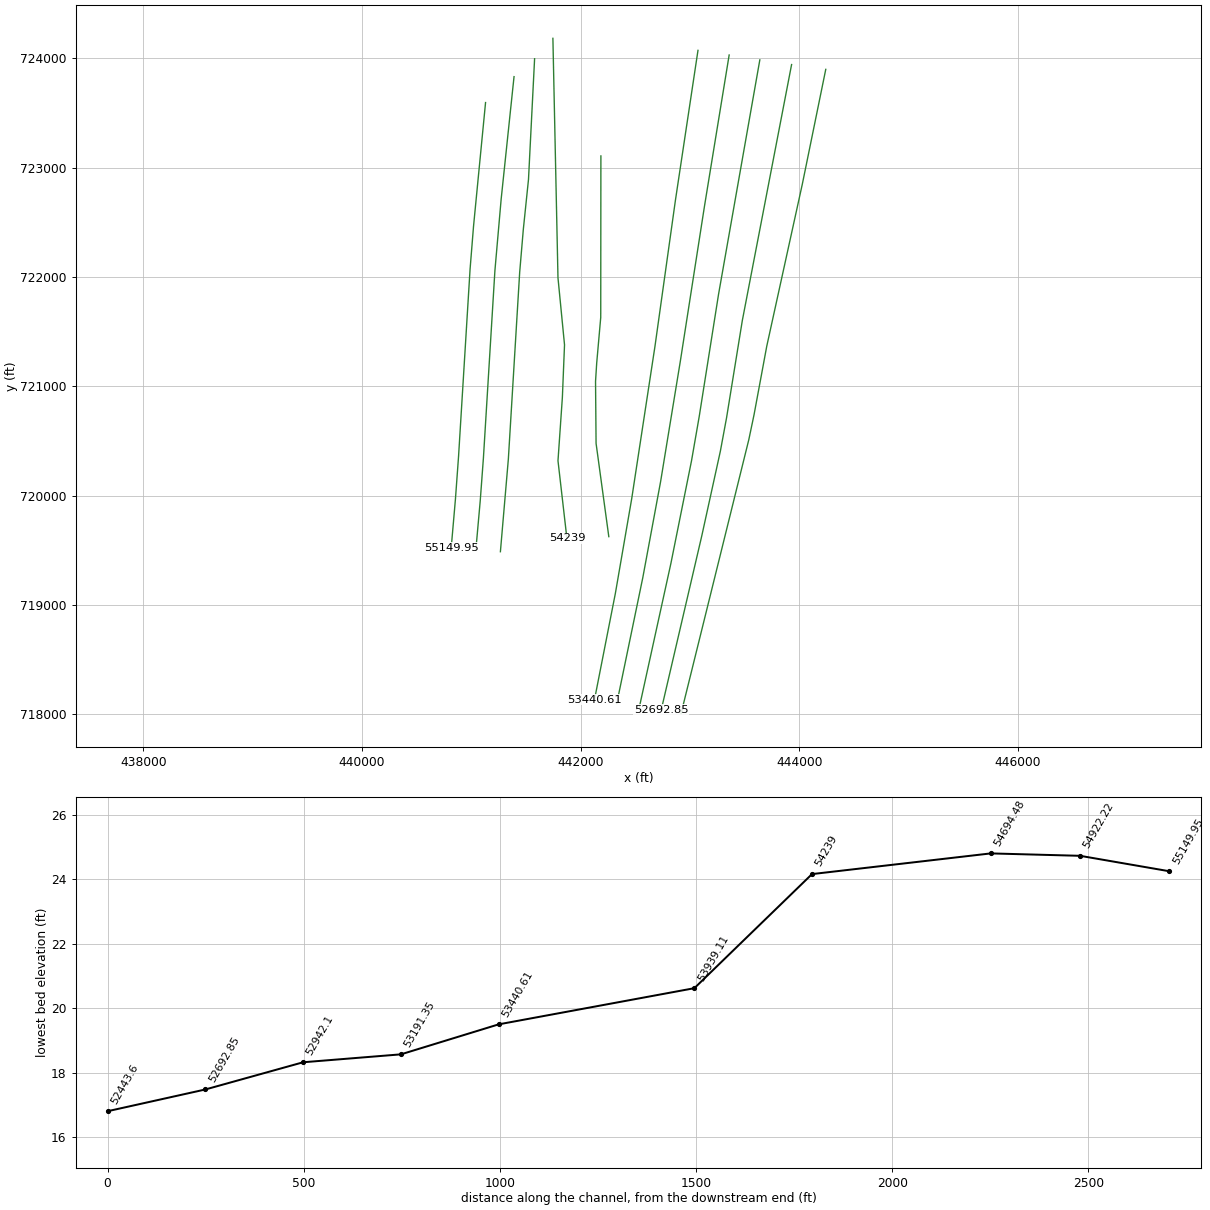
HEC-RAS study 691_ras.prj: 691

--- 691_ras.g01 (geometry) --- (continued)

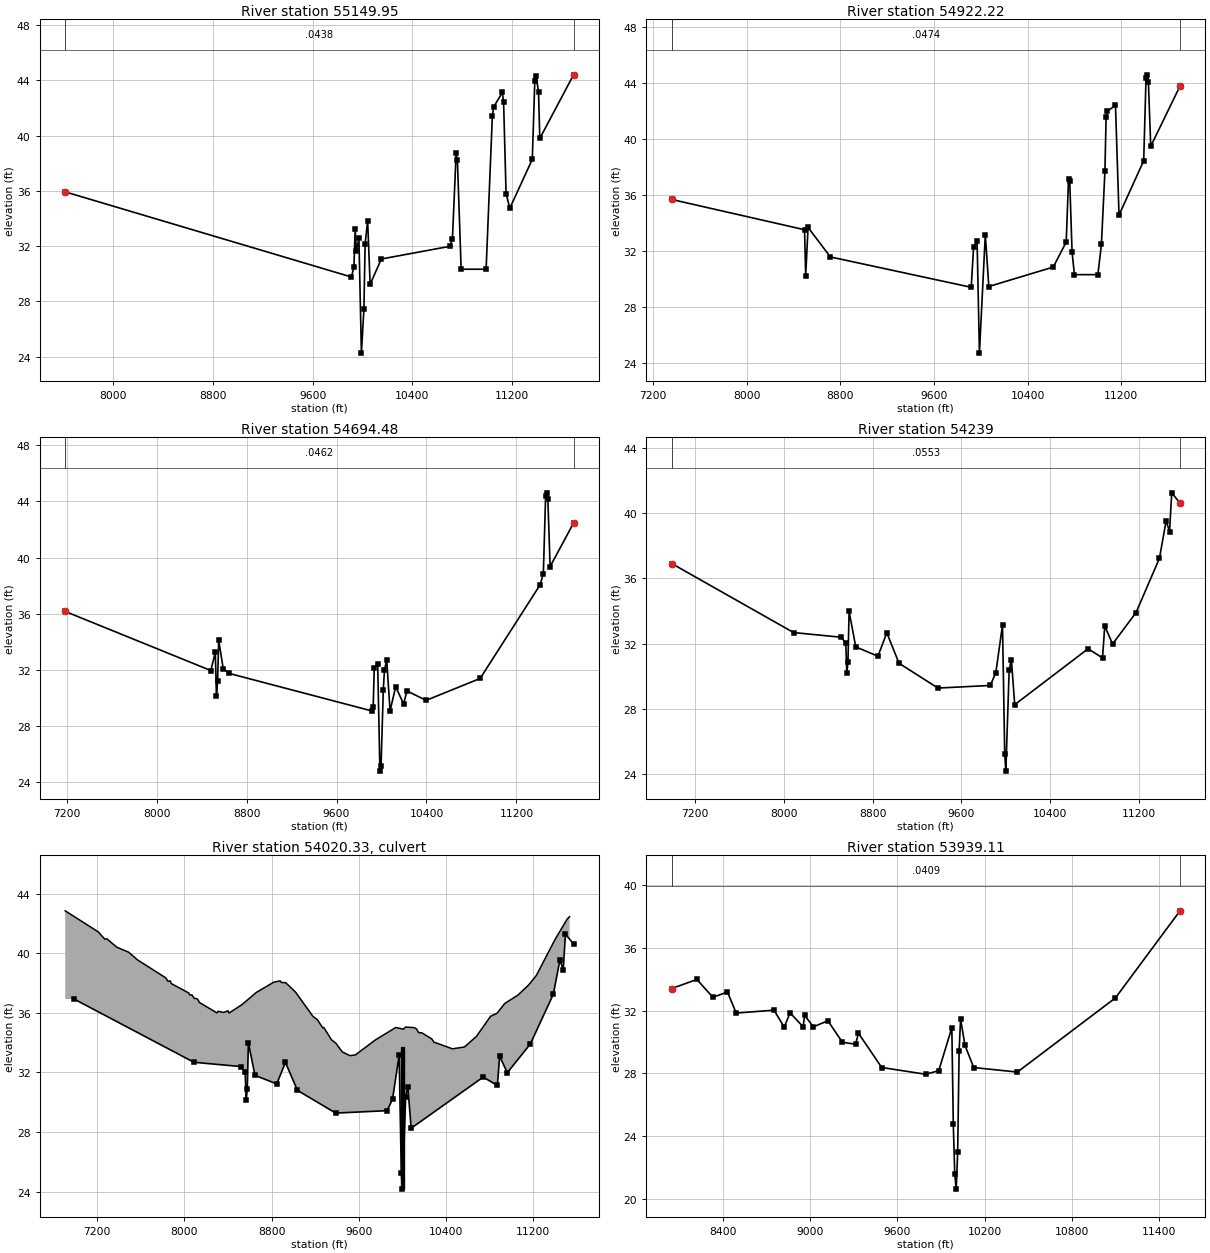
Type RM Length L Ch R = 1 ,55149.95,227.738900,227.738900,227.738900
XS GIS Cut Line= 6
 441130.32418716723596.557697996441020.518043667722467.133000493
440988.682812005722072.260960966440883.475839525720362.275969133
 440854.60380742 719966.21396406440816.210473269719524.876855835
#Sta/Elev= 30
7612.53435.926229912.25629.762539932.29130.489479942.30833.214389952.32631.61545
9972.36132.575639992.39624.2499510012.4327.4420110022.4532.1765710042.4833.83764
10062.5129.2337810152.6631.0665410703.64 31.984310723.68 32.522810753.7438.75683
10763.7638.2212810793.8230.3257310994.3130.3257311044.4441.3966811054.4742.06643
11124.6543.1277211134.6842.4620511154.7335.7975511184.8134.7413611365.4138.28032
11385.4943.9272511395.5344.32714 11415.643.1634211425.6439.7920711696.7844.40196
#Mann= 3 , 0 , 0
7612.534  0.0438       07612.534  0.0438       011696.78  0.0438       0
#XS Ineff= 2 , 0
       08783.475        10759.05       0
Bank Sta=7612.534,11696.78
Exp/Cntr=0.3,0.1

Type RM Length L Ch R = 1 ,54922.22,227.738800,227.738800,227.738800
XS GIS Cut Line= 6
441390.893876851723833.726730645441273.058944166722713.085781887
441215.893055707 722058.65185222441111.015980512 720349.14551124
 441081.60353899719953.123725995441041.681971073719506.011143804
#Sta/Elev= 30
7360.17435.685298495.116  33.5278505.16130.264198525.25233.691188716.11631.58756
9919.14829.422699939.18332.265369969.23532.74106 9989.2724.7299510039.3533.18049
 10069.429.4798410620.3430.8667110730.5632.65453 10750.637.1676910760.6237.01046
10780.6631.94317 10800.730.3257311001.2130.3257311031.2932.4756411061.3737.70899
 11071.441.5666311081.4341.9910711151.6242.38568 11181.734.5693311392.4538.44105
11412.5344.3706911422.57 44.570811432.6144.0792111452.6939.4768311702.6743.77076
#Mann= 3 , 0 , 0
7360.174  0.0474       07360.174  0.0474       011702.67  0.0474       0
#XS Ineff= 2 , 0
       08936.076         10759.3       0
Bank Sta=7360.174,11702.67
Exp/Cntr=0.3,0.1

Type RM Length L Ch R = 1 ,54694.48,455.477700,455.477700,455.477700
XS GIS Cut Line= 6
441578.968161821723997.411916137441523.148358345722893.617615402
441475.682404876722434.881902322441442.533652514722043.663956478
441338.947881609720335.864929721441266.129131556719487.575147569
#Sta/Elev= 30
7186.69336.168378481.63731.963538521.845 33.25638531.89430.132988541.94331.21024
8551.99134.102478592.18732.104048642.43231.762649915.89629.084529925.91329.38983
 9935.9332.16877 9965.9832.445629986.01424.804499996.03125.1361610016.0630.58828
10026.08 31.968310046.1132.7331410076.1629.0872110126.2430.8128610196.3529.58687
10226.3930.5113810396.6629.8406310877.5931.3998611409.3838.0462911439.5138.84145
 11459.644.3511911469.6444.6096511479.6944.1621411499.7739.36382 11708.142.45513
#Mann= 3 , 0 , 0
7186.693  0.0462       07186.693  0.0462       0 11708.1  0.0462       0
#XS Ineff= 2 , 0
       09088.026         10764.2       0
Bank Sta=7186.693,11708.1
Exp/Cntr=0.3,0.1

Type RM Length L Ch R = 1 ,   54239,299.886600,299.886600,299.886600
XS GIS Cut Line= 6
  441746.3903054724184.151999325441792.856022209721993.737483695
441852.722661555721380.332809687441833.176954359720901.282751009
 441792.95490253720319.680011779441874.355222344719611.084397346
#Sta/Elev= 30
6987.94936.919078087.30932.675868517.41532.388448557.42632.035818567.42930.17647
8577.43230.890588587.43533.978098647.45131.797548847.507 31.22338927.52932.66282
9037.559 30.79059388.73129.265769860.58929.42714 9910.6330.214859970.67833.14682
9990.69425.21747 10000.724.1623910030.7330.3702410050.7531.0188910080.7728.24761
   1074231.6793810872.4531.1205510892.5833.0832110963.0431.9731711174.4233.90244
 11385.837.24441 11446.239.5568411476.3938.8704511496.5241.2623111570.9340.63332
#Mann= 3 , 0 , 0
6987.949  0.0553       06987.949  0.0553       011570.93  0.0553       0
#XS Ineff= 2 , 0
       09299.266        10768.14       0
Bank Sta=6987.949,11570.93
Exp/Cntr=0.3,0.1

Type RM Length L Ch R = 2 ,54020.33,,,
Bridge Culvert--1,0,-1,-1, 0
Deck Dist Width WeirC Skew NumUp NumDn MinLoCord MaxHiCord MaxSubmerge Is_Ogee
127.443,45,2.6,0, 60, 60, , , 0.95, 0, 0,0,,
 6906.56 7209.50 7269.51 7289.51 7379.51 7489.52 7569.52 7829.52 7849.52 7869.52
 7879.52 8039.53 8049.53 8069.53 8089.53 8119.53 8139.53 8299.53 8309.53 8359.53
 8399.53 8409.53 8529.53 8659.53 8819.53 8879.53 8889.53 8929.53 9019.53 9179.54
 9219.54 9269.54 9279.54 9349.54 9389.54 9449.54 9519.54 9569.54 9749.54 9939.55
10009.5510029.5510109.5510129.5510149.5510179.5510269.5510289.5510459.5510569.55
10679.5510809.5510869.5510939.5511059.7811160.0011230.1611403.7711512.2611534.78
   42.84   41.43   40.94   40.96   40.40   40.06   39.55   38.34   38.11   38.14
   37.96   37.33   37.19   37.20   36.97   36.93   36.68   35.99   36.10   36.02
   36.13   35.98   36.55   37.36   38.05   38.14   38.03   38.02   37.39   35.76
   35.54   34.99   35.01   34.19   33.96   33.37   33.12   33.17   34.16   35.01
   34.90   35.04   35.00   34.92   34.67   34.65   34.25   34.03   33.58   33.70
   34.41   35.76   35.97   36.62   37.18   37.87   38.51   40.95   42.28   42.45
                                                                                
                                                                                
                                                                                
                                                                                
                                                                                
                                                                                
 6906.56 7209.50 7269.51 7289.51 7379.51 7489.52 7569.52 7829.52 7849.52 7869.52
 7879.52 8039.53 8049.53 8069.53 8089.53 8119.53 8139.53 8299.53 8309.53 8359.53
 8399.53 8409.53 8529.53 8659.53 8819.53 8879.53 8889.53 8929.53 9019.53 9179.54
 9219.54 9269.54 9279.54 9349.54 9389.54 9449.54 9519.54 9569.54 9749.54 9939.55
10009.5510029.5510109.5510129.5510149.5510179.5510269.5510289.5510459.5510569.55
10679.5510809.5510869.5510939.5511059.7811160.0011230.1611403.7711512.2611534.78
   42.84   41.43   40.94   40.96   40.40   40.06   39.55   38.34   38.11   38.14
   37.96   37.33   37.19   37.20   36.97   36.93   36.68   35.99   36.10   36.02
   36.13   35.98   36.55   37.36   38.05   38.14   38.03   38.02   37.39   35.76
   35.54   34.99   35.01   34.19   33.96   33.37   33.12   33.17   34.16   35.01
   34.90   35.04   35.00   34.92   34.67   34.65   34.25   34.03   33.58   33.70
   34.41   35.76   35.97   36.62   37.18   37.87   38.51   40.95   42.28   42.45
                                                                                
                                                                                
                                                                                
                                                                                
                                                                                
                                                                                
BR Coef=-1 , 0 , 0 ,, 0 ,,,0.8,-1,,0,
WSPro=,,,, 1 ,,,, 0 ,,,, 0 ,,,,-1 ,-1 ,-1 , 0 , 0 , 0 , 0 , 0
Multiple Barrel Culv=2,9.5,9.5,45,0.013,0.7,1,8,3,24.2,20.7,2,Culvert #1, 0, 127.443
 9990.50 9990.5010009.5010009.50
Culvert Bottom n=0.013
BC Design=,, 0 ,, 0 ,,,,,,

Type RM Length L Ch R = 1 ,53939.11,498.505900,498.505900,498.505900
XS GIS Cut Line= 6
442185.463235825723108.370619804442184.020229906721631.188171268
442147.001727283  721212.0459093442136.498799413721045.940069884
442141.392722994720478.830021486442257.880870044719625.466609135
#Sta/Elev= 30
8048.72333.403928222.09333.980848332.09432.843068432.09433.185598492.09431.83948
8752.09432.024418822.09430.940728862.09431.854118952.09430.965538962.09431.69793
9022.094 30.96159122.09431.347849222.094 29.97569312.09429.857349332.094 30.5563
9492.09428.369879793.21927.94135 9883.5228.161769973.77830.902089983.79524.76152
9993.81221.5600510003.83 20.619510013.8522.9633510023.8729.4331410033.8931.45234
10063.9629.7847310124.0728.3678710424.0828.0797111098.1432.8068711541.5438.35527
#Mann= 3 , 0 , 0
8048.723  0.0409       08048.723  0.0409       011541.54  0.0409       0
#XS Ineff= 2 , 0
       09271.857        10746.68       0
Bank Sta=8048.723,11541.54
Exp/Cntr=0.3,0.1

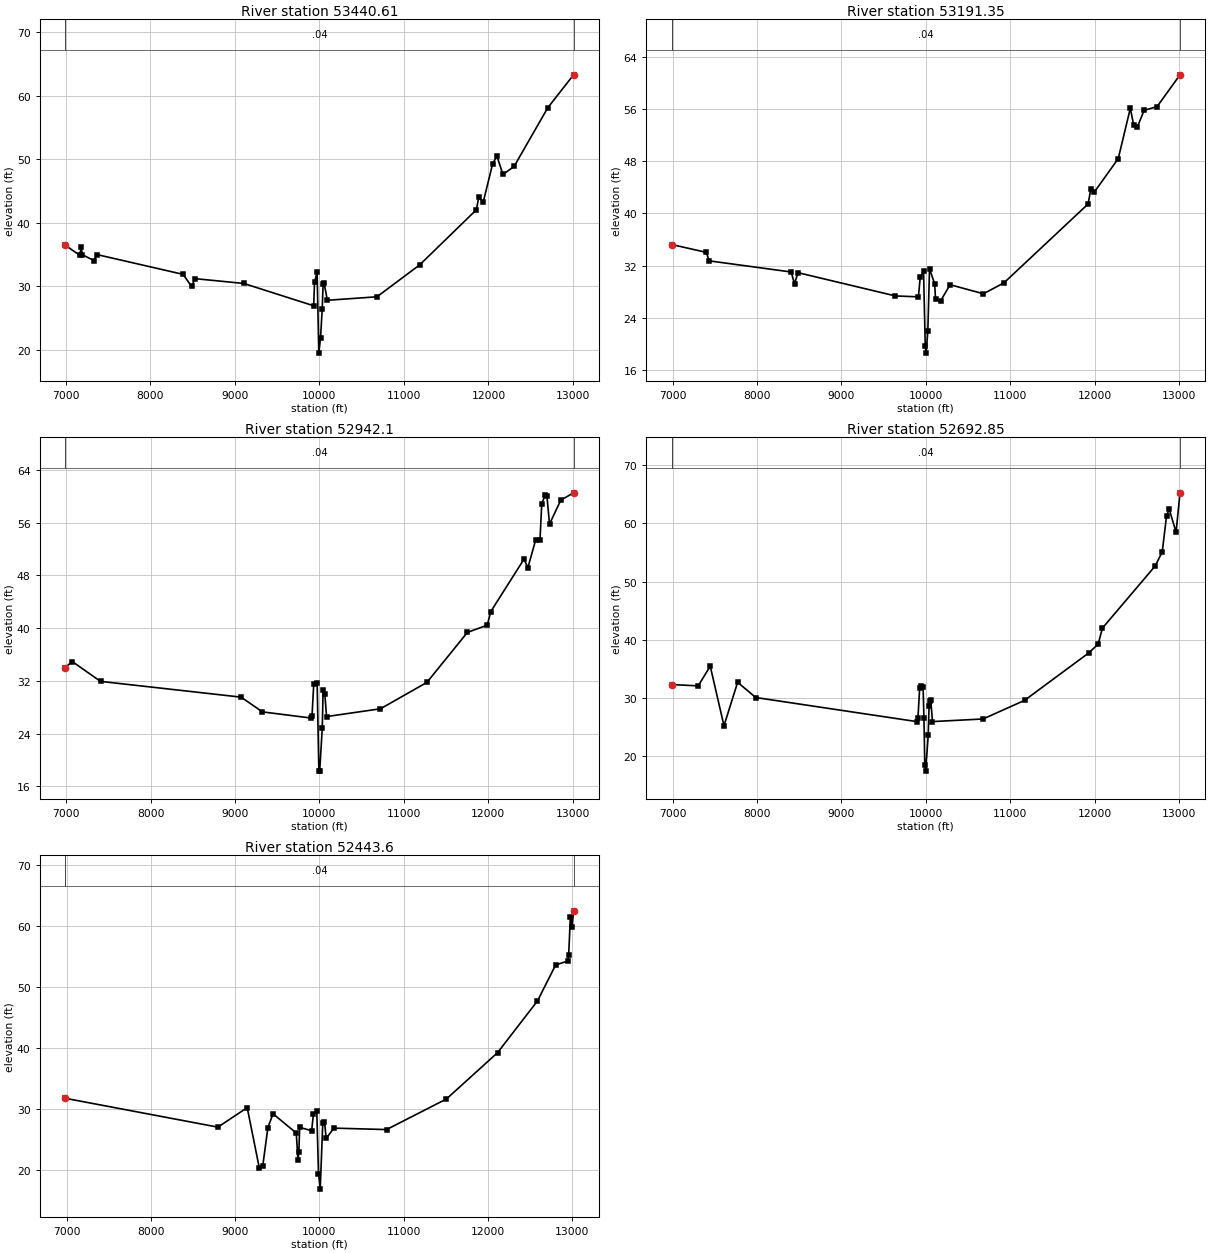
Type RM Length L Ch R = 1 ,53440.61,249.252900,249.252900,249.252900
XS GIS Cut Line= 6
443073.722393488724074.032165694442867.840031662722706.704123399
  442680.3448957721367.976970922442467.184459208719971.532575265
442317.745324358719105.631356069442127.204935825718135.513959306
#Sta/Elev= 30
 6992.7236.468497163.70234.89379 7183.4536.204837194.04834.983347335.66334.03487
7366.00935.000518387.28731.88416  8488.329.989298528.70531.207499104.30930.45392
9932.67826.943539942.799 30.6571 9973.1632.21858  9993.419.4972110013.6521.86445
 10033.926.4584710044.0230.3314110054.15  30.58810094.6527.8075310681.2128.35448
11187.0533.3749111856.7342.02473 11887.244.0229511937.9943.2006612049.7949.23973
12100.6950.4951712171.9547.5878212304.2948.8557912701.8158.0641213007.2863.25613
#Mann= 3 , 0 , 0
 6992.72    0.04       0 6992.72    0.04       013007.28    0.04       0
#XS Ineff= 2 , 0
       09202.856                       0
Bank Sta=6992.72,13007.28
Exp/Cntr=0.3,0.1

Type RM Length L Ch R = 1 ,53191.35,249.253000,249.253000,249.253000
XS GIS Cut Line= 6
443358.884919753724031.658490114443133.618068533722651.831315753
442911.560830257721226.345180063 442731.65157942720128.481116596
442568.872249786719250.497905586442330.634736348718099.044614479
#Sta/Elev= 30
6988.94635.229147400.98834.015347431.38532.724018404.08231.012458444.58329.19803
8485.08330.909379638.83727.341329912.12227.198869933.51930.202199972.90131.09575
9993.16119.6496710003.2918.5654410023.55 21.930410043.81 31.5096 10104.6 29.1956
10114.7326.8657410175.5126.5781410286.9529.0624710682.1327.6719810925.4829.34638
11922.4241.4467511955.5543.8165311993.8443.2296712279.52 48.410112422.3656.12917
12463.2153.4992812504.0953.1924812585.8755.8141212739.1956.3775113011.0561.25921
#Mann= 3 , 0 , 0
6988.946    0.04       06988.946    0.04       013011.05    0.04       0
#XS Ineff= 2 , 0
       09150.648                       0
Bank Sta=6988.946,13011.05
Exp/Cntr=0.3,0.1

Type RM Length L Ch R = 1 , 52942.1,249.252900,249.252900,249.252900
XS GIS Cut Line= 6
443639.471586503723987.139514185443261.923176248721843.188098483
443084.491089575720721.681582399443014.665958523720320.462767754
442825.548590808 719379.00522337442537.657621513718067.169338039
#Sta/Elev= 30
6988.48934.035527071.90334.943137407.019 31.93259072.24329.542779325.74727.30479
9902.92926.370979913.04526.728839933.27731.506739973.74131.636219993.97318.31952
10004.0918.3940410034.4524.8666210044.5630.68992 10064.829.9727610085.0426.59336
10723.9127.7765811274.2731.7796511754.3839.3688411989.6640.4607512030.5742.51735
12424.5150.4710312470.6149.17193 12562.853.3901212614.2153.39769 12634.758.84113
12675.6860.2493812696.1660.0385712726.8955.7923412860.07 59.4127 13011.560.53448
#Mann= 3 , 0 , 0
6988.489    0.04       06988.489    0.04       0 13011.5    0.04       0
#XS Ineff= 2 , 0
       09100.254                       0
Bank Sta=6988.489,13011.5
Exp/Cntr=0.3,0.1

Type RM Length L Ch R = 1 ,52692.85,249.252900,249.252900,249.252900
XS GIS Cut Line= 6
 443930.02448684723944.201918214443479.450945543721603.543148094
443335.038272604720712.455526801443278.091376259720405.921924924
 443107.99000774719630.760802126442737.258696963  718039.6643898
#Sta/Elev= 30
6987.23632.31862  7301.932.098357444.37335.483297607.26325.253287768.975 32.7129
7983.89530.099429896.65125.960569906.76726.645129926.998 31.7102 9947.2332.04664
9967.46131.923539977.57726.555489987.69318.513099997.80817.4744410028.1423.61267
10038.2528.7247810048.3629.5080710058.4729.64333 10078.725.9702910678.37 26.4205
11169.6729.6055711929.1637.7284612042.1139.2491812093.4542.0089412719.7952.68022
12802.3855.1069912853.27 61.232512884.0762.4336812966.2258.4657913012.7765.20962
#Mann= 3 , 0 , 0
6987.236    0.04       06987.236    0.04       013012.77    0.04       0
#XS Ineff= 2 , 0
       09051.135                       0
Bank Sta=6987.236,13012.77
Exp/Cntr=0.3,0.1

Type RM Length L Ch R = 1 , 52443.6,249.253000,249.253000,249.253000
XS GIS Cut Line= 6
444242.626162942723900.310401381444027.932269102722848.912329256
443702.775796792721367.469646978443586.807447515720742.255760656
 443538.73508456720512.999128824442919.301314086718008.698425495
#Sta/Elev= 30
6980.12131.713738794.29126.976769142.62630.178199286.05820.288889327.01520.57117
9388.378 26.9165 9449.7429.165359725.32326.012439745.70521.590669755.89622.88223
9766.08726.943629908.38726.382179928.70129.06041 9969.3329.633739989.64419.31743
10009.9616.7988910040.4527.6910610060.7827.83858 10081.125.1356210172.5626.81415
10797.9226.5773711509.31 31.594712117.4839.2097912591.1747.6888412807.43 53.6061
12951.5954.2517912961.8955.1884312982.4961.5262913003.08 59.758213019.8762.49179
#Mann= 3 , 0 , 0
6980.121    0.04       06980.121    0.04       013019.87    0.04       0
#XS Ineff= 2 , 0
       08995.458                       0
Bank Sta=6980.121,13019.87
Exp/Cntr=0.3,0.1