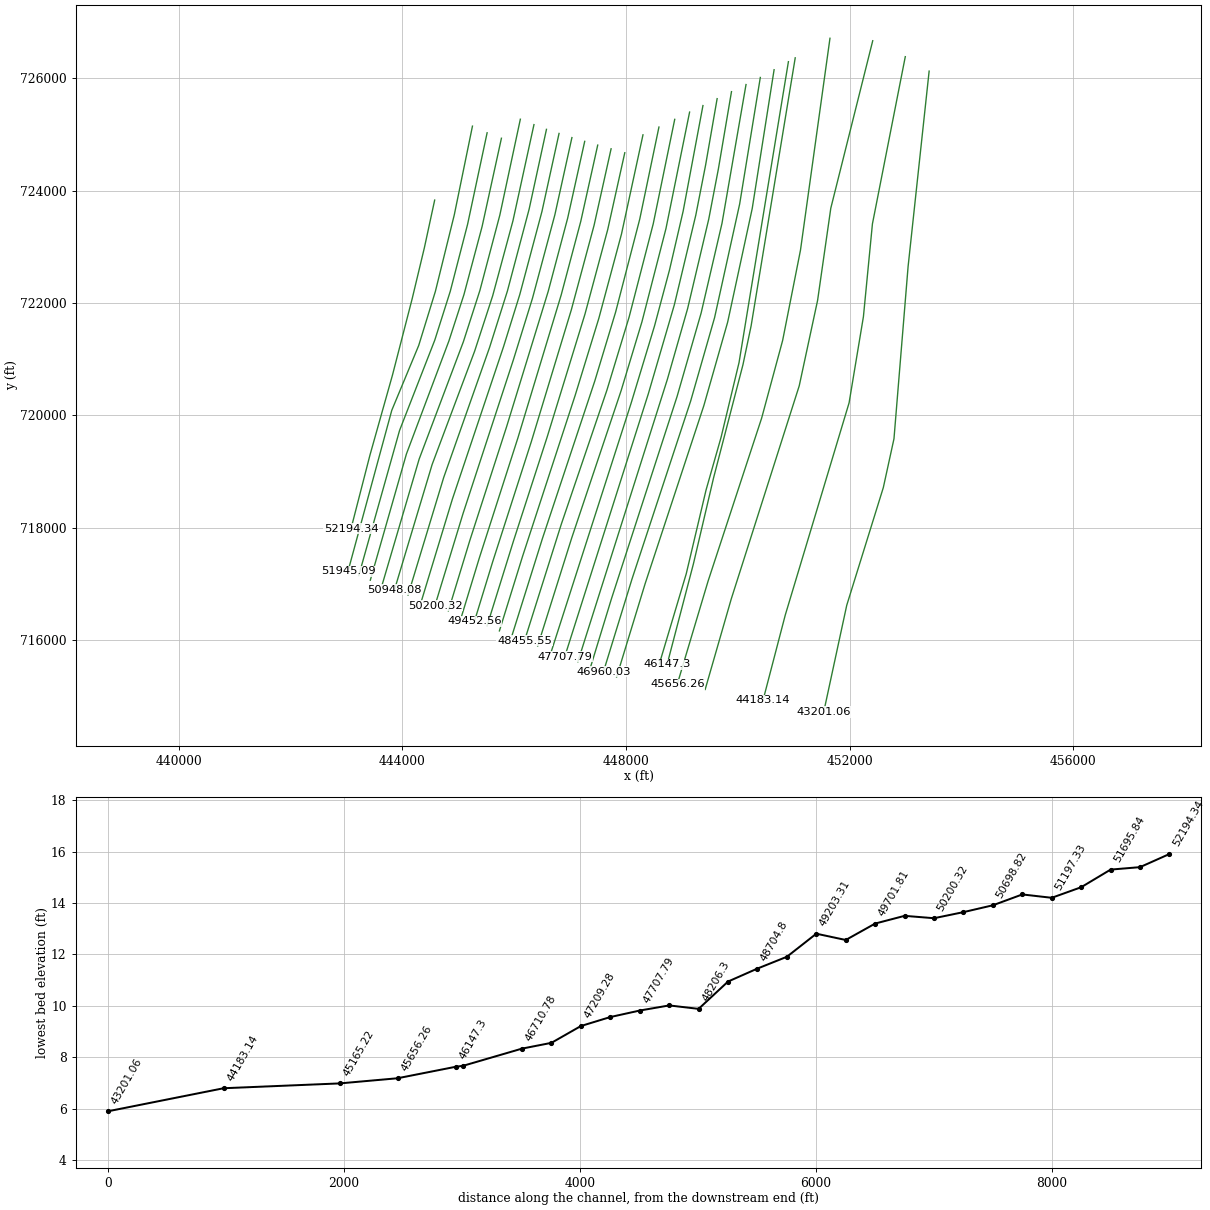
HEC-RAS study 691_ras.prj: 691

--- 691_ras.g01 (geometry) --- (continued)

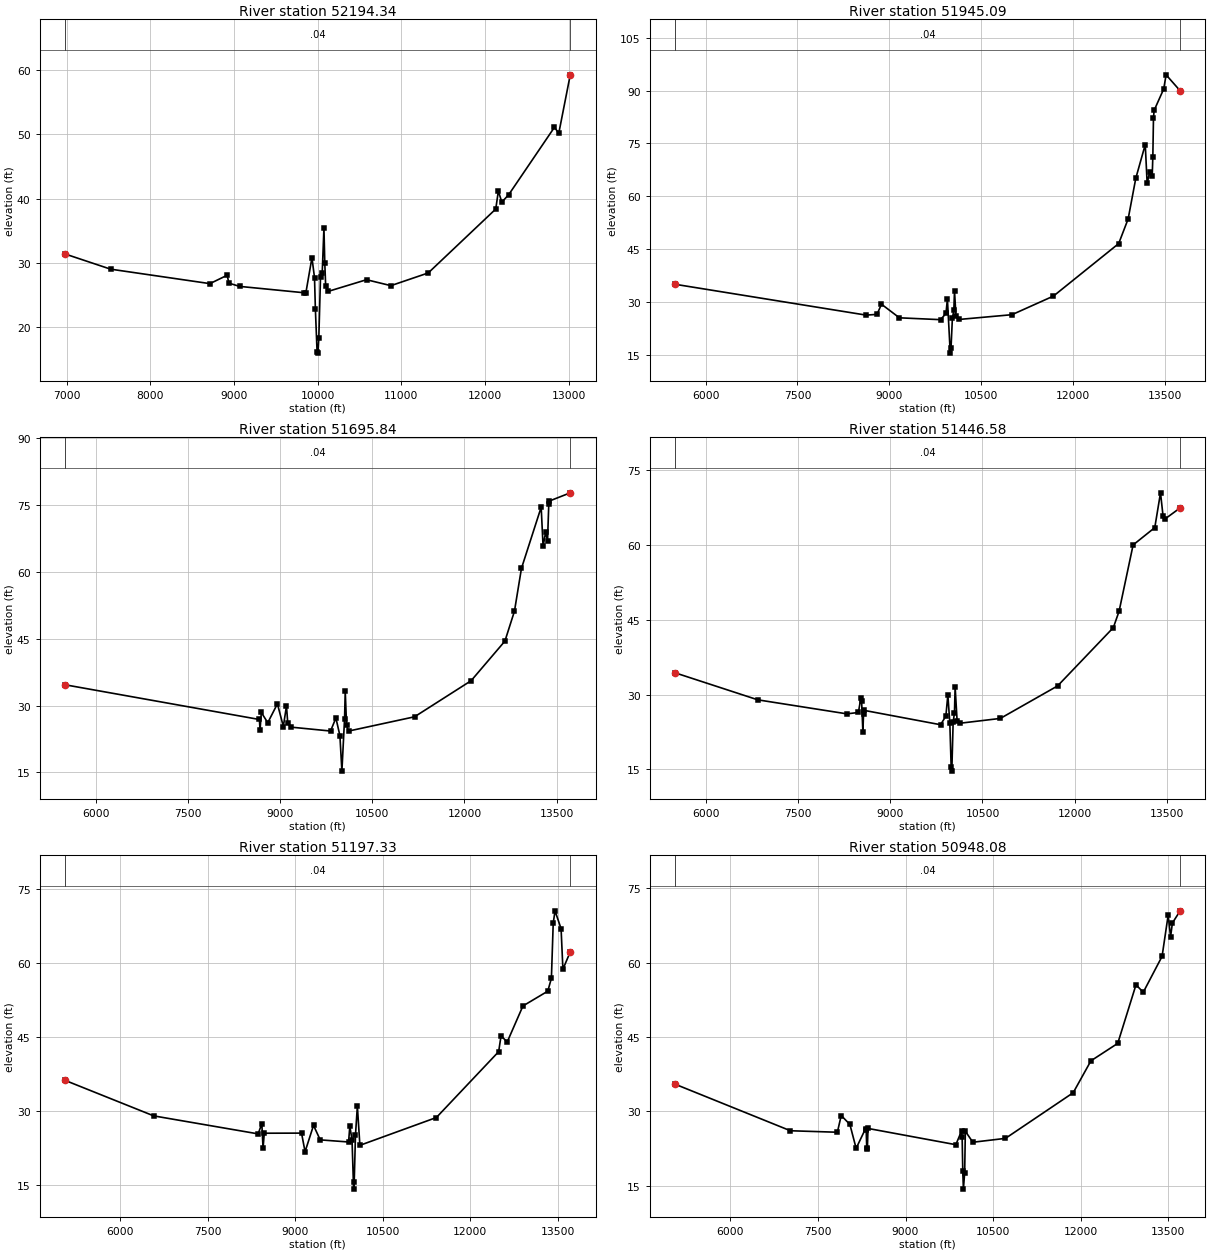
Type RM Length L Ch R = 1 ,52194.34,249.252900,249.252900,249.252900
XS GIS Cut Line= 6
444579.196415977723833.516419393444394.517266484722982.974233671
  444175.6852846722072.904213041443824.175395183 720716.47693086
443422.425918951719295.137959989443083.022241613717982.014064161
#Sta/Elev= 30
 6979.4431.361537524.80228.991778711.55826.739418918.00728.043788938.67426.81642
9066.42226.308369839.11425.315959859.71925.347069931.76930.784139962.49827.67351
9972.74122.818039993.22616.0755310003.4715.9097910013.7218.1935310034.2227.79994
10054.7228.4133210075.2235.4446910085.4729.8799410095.7826.4115810126.77 25.5342
10584.2827.3495310875.7326.4241511322.4628.4047712129.7438.3645412160.7641.16667
12202.1339.43629 12284.740.60117 12831.751.1043312883.31 50.165813020.5659.27613
#Mann= 3 , 0 , 0
 6979.44    0.04       0 6979.44    0.04       013020.56    0.04       0
#XS Ineff= 2 , 0
       08921.603                       0
Bank Sta=6979.44,13020.56
Exp/Cntr=0.3,0.1

Type RM Length L Ch R = 1 ,51945.09,249.252900,249.252900,249.252900
XS GIS Cut Line= 6
445254.755114764 725150.15404807444929.948936582723571.155317202
444591.526599318722206.867984474444293.536878794721244.500093177
443811.931206584720089.902418688443028.793388605717222.559517846
#Sta/Elev= 30
5499.419 34.97538623.16926.202518799.92926.416518872.99929.303659165.79425.43771
9837.20624.912129926.69226.686189949.66830.807629996.17815.3981910009.1616.99431
10031.2825.3927610054.4327.53819 10065.833.1027610089.8625.8224610133.2624.96053
11003.7326.3230811682.2631.6220612747.5346.5440412902.54 53.583313026.5465.07526
13181.5574.6967113212.5563.6288413253.8466.8982913295.1165.7207913305.4371.27905
13315.7582.1719513326.0684.38909 13482.890.49803 13522.194.5177613751.6189.97817
#Mann= 3 , 0 , 0
5499.419    0.04       05499.419    0.04       013751.61    0.04       0
#XS Ineff= 2 , 0
       08776.872                       0
Bank Sta=5499.419,13751.61
Exp/Cntr=0.3,0.1

Type RM Length L Ch R = 1 ,51695.84,249.253000,249.253000,249.253000
XS GIS Cut Line= 6
445516.841963738725031.580319971 445167.71802333723402.373488918
444858.339520097722211.053851217444581.119794905721340.315815225
443951.448476315719732.274119332443221.544341505717147.135231912
#Sta/Elev= 30
5497.56134.653248661.74826.873418672.18124.516128693.12728.451048797.85626.14915
8955.20430.389539051.55225.299629102.64829.900289123.82226.033769175.14325.16173
9820.34224.288659907.258 27.20769972.44523.2840910005.0415.3022310048.5227.06824
 10059.433.2757410081.1425.5468110113.7624.2796211187.9327.47874 12109.235.56808
12659.23 44.441312814.5951.1524112928.5260.74211 13249.6 74.458113280.6165.64458
13321.9668.8631813352.9866.9293213373.6575.2604313383.9975.8380513722.9377.66925
#Mann= 3 , 0 , 0
5497.561    0.04       05497.561    0.04       013722.93    0.04       0
#XS Ineff= 2 , 0
       08648.204                       0
Bank Sta=5497.561,13722.93
Exp/Cntr=0.3,0.1

Type RM Length L Ch R = 1 ,51446.58,249.252900,249.252900,249.252900
XS GIS Cut Line= 6
445772.624083459 724934.65899685445426.887290806723361.820867956
445102.282536715722149.882907897444833.771118581721326.098512903
444073.932363242719313.091591462443428.398016244717066.192489639
#Sta/Elev= 30
5495.07734.364346845.277 28.92648292.60226.117738480.33426.388798522.157 29.3989
8532.63728.782578553.59722.495158564.07826.101518574.558 26.81329817.86123.93306
9904.02125.660889936.33129.930259968.64124.278329990.18115.4444510000.9514.61638
 10022.524.4442210044.0626.3204710054.8331.5301510087.1624.6951110141.0424.24386
10790.5725.1979111722.9731.7287412629.6943.4326212723.1746.7161812951.4360.03112
13304.1163.5090713397.3570.4944913438.7965.8311713469.8765.2389613717.0867.47098
#Mann= 3 , 0 , 0
5495.077    0.04       05495.077    0.04       013717.08    0.04       0
#XS Ineff= 2 , 0
       08539.124                       0
Bank Sta=5495.077,13717.08
Exp/Cntr=0.3,0.1

Type RM Length L Ch R = 1 ,51197.33,249.253000,249.253000,249.253000
XS GIS Cut Line= 6
446110.921929747725273.213251948445744.635930389723568.402339086
445388.012652934722225.989335805445092.151744306721310.935216263
444301.447348714719221.802090853443639.819418997716983.462375492
#Sta/Elev= 30
5050.10336.226966571.46129.032028361.63425.390088424.482 27.48228445.431 22.4517
 8466.3825.524249105.57625.545869165.79421.771429310.86327.110059425.80424.17698
9911.94723.749499933.48826.929039971.22524.22577 9998.1114.2047410008.8915.71042
10030.4525.1668810062.7931.0001510105.9123.0718711417.7628.7033912485.4842.03319
12527.1845.2741612631.4343.9710512902.0151.2889713327.8254.2823513390.1256.89068
13421.2768.0476213452.4270.5510513556.2666.9240813587.3958.7176613713.3962.23332
#Mann= 3 , 0 , 0
5050.103    0.04       05050.103    0.04       013713.39    0.04       0
#XS Ineff= 2 , 0
       08430.015                       0
Bank Sta=5050.103,13713.39
Exp/Cntr=0.3,0.1

Type RM Length L Ch R = 1 ,50948.08,249.252900,249.252900,249.252900
XS GIS Cut Line= 6
446354.279535323725176.848551631 445977.97022438723461.933623478
445616.399751186722130.088628575445293.750883847721143.888271943
444533.648872048719125.732148618 443860.89896518716896.952987894
#Sta/Elev= 30
5048.29235.522237027.84326.114137832.157 25.81427898.01129.189228046.48627.39471
 8153.6522.565798315.24626.542988325.70926.357238336.171   22.388346.63422.60397
8357.09626.581739862.57923.302159959.89126.051579970.70424.828639981.51717.96091
9992.32914.3354510013.9417.6762110025.4426.0176610154.3323.7958410713.2524.57772
 11874.133.7866312178.07 40.2261 12637.743.7475812950.4455.5651713075.2554.06278
13397.6661.3066513501.6669.6039913543.2665.2529513574.4668.03327 13707.470.49062
#Mann= 3 , 0 , 0
5048.292    0.04       05048.292    0.04       0 13707.4    0.04       0
#XS Ineff= 2 , 0
       08320.067                       0
Bank Sta=5048.292,13707.4
Exp/Cntr=0.3,0.1

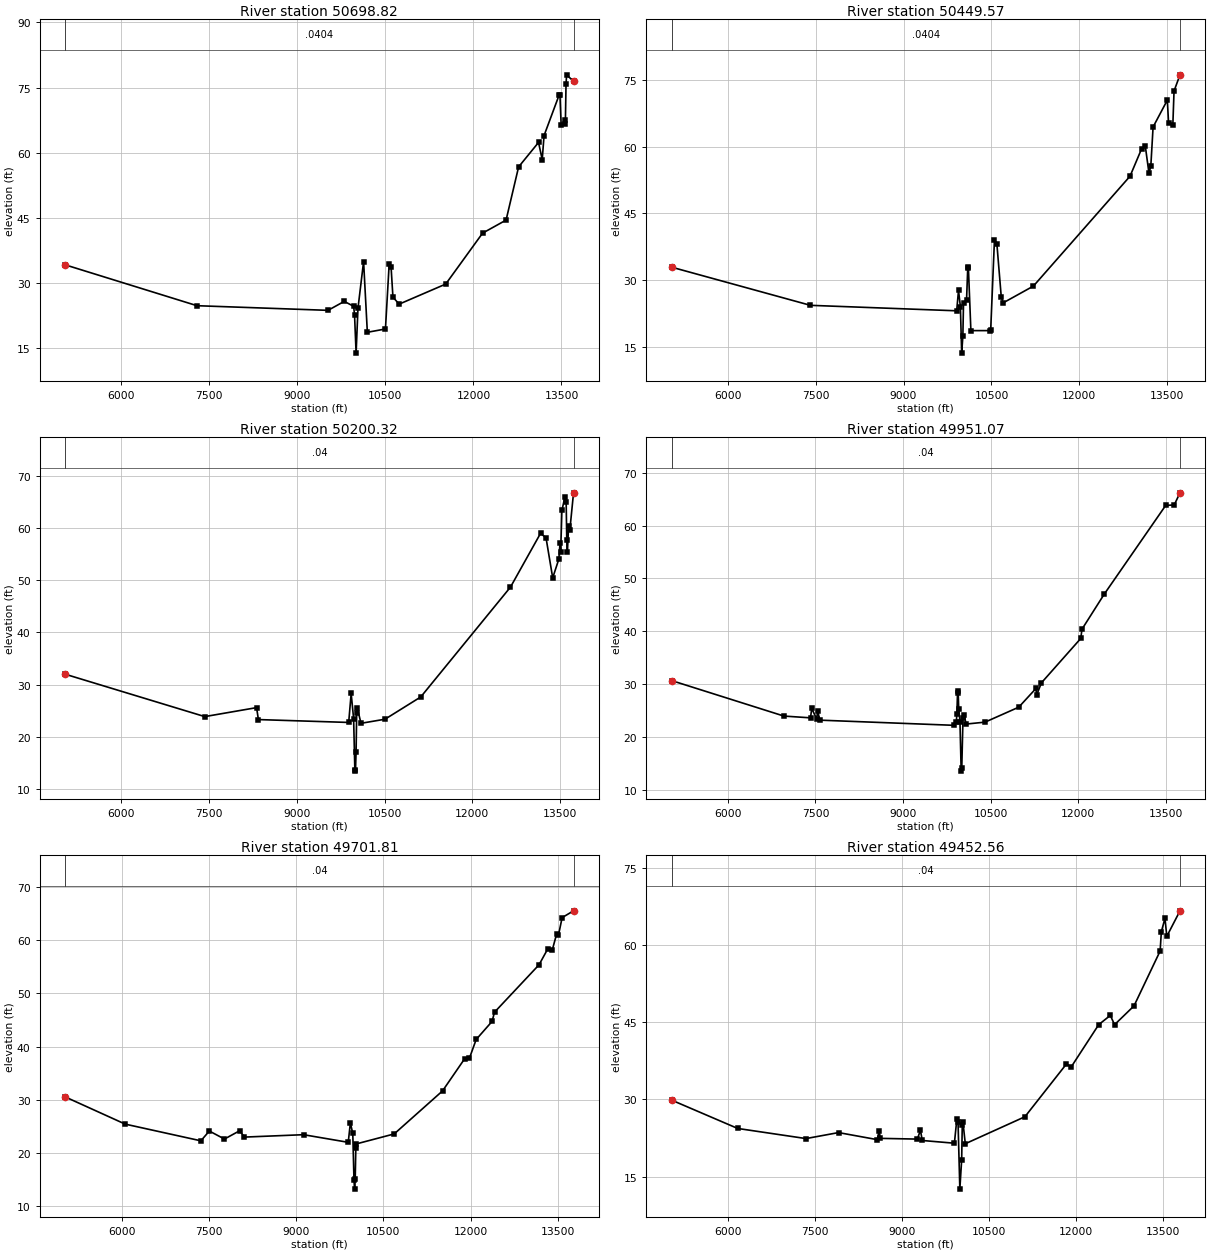
Type RM Length L Ch R = 1 ,50698.82,249.252900,249.252900,249.252900
XS GIS Cut Line= 6
446577.942896664725092.929871172446268.325292587723673.729535162
445879.202036947722212.869545206445560.838202119 721210.10504511
 444740.77181527718895.478130326444102.959649771 716802.23358956
#Sta/Elev= 30
5044.38534.224437290.17424.823829522.14323.755269798.62225.816159958.12824.69614
 9973.8622.7981810000.6613.9135910032.5924.2275810128.3534.97463 10192.218.70706
10500.6619.4686710564.62 34.520210596.52 33.729810628.3626.7855710734.5125.18487
11527.8829.8036612155.7941.5173812556.0244.5186312769.3556.75367 13109.162.38637
13171.6858.4402613202.9763.9555413463.1673.4107313473.5673.2965913494.3766.36098
13556.7866.5553813567.1867.6586713577.5975.9213313587.9977.9371813705.2976.43818
#Mann= 3 , 0 , 0
5044.385  0.0404       05044.385  0.0404       013705.29  0.0404       0
#XS Ineff= 2 , 0
       08190.812                       0
Bank Sta=5044.385,13705.29
Exp/Cntr=0.3,0.1

Type RM Length L Ch R = 1 ,50449.57,249.253000,249.253000,249.253000
XS GIS Cut Line= 6
446802.893331379725019.811190382446496.956617653723629.636130497
446101.187286019722153.114706516445811.795902252721227.750668988
444895.156187832718507.567624107444345.760279596716707.224647433
#Sta/Elev= 30
5042.77632.94159 7410.9524.377389906.39123.149239938.03527.73467 9969.6824.09686
9991.75513.6466910011.8717.3946210023.27 24.884510075.1425.6368310096.2333.07893
10106.7732.7344310148.9518.7007510476.5318.70075 10487.118.8693510551.2739.12656
10592.8238.1347610666.83 26.331710698.5424.9236711216.2828.7008512864.8653.36856
13063.21 59.546113125.7960.0882813188.37  54.02813219.6655.6481713258.2964.41468
13501.2670.4510313522.1265.4195413595.0764.7600613615.8872.4925113717.5976.12896
#Mann= 3 , 0 , 0
5042.776  0.0404       05042.776  0.0404       013717.59  0.0404       0
#XS Ineff= 2 , 0
       08016.436                       0
Bank Sta=5042.776,13717.59
Exp/Cntr=0.3,0.1

Type RM Length L Ch R = 1 ,50200.32,249.252900,249.252900,249.252900
XS GIS Cut Line= 6
447032.784665883724945.850010082446727.813220382723570.426083177
446327.445173532 722084.13229163445984.074988127720982.314849019
445085.798527956718250.962189019444584.016541481716613.993936285
#Sta/Elev= 30
5040.87931.99735 7426.75 23.86728312.24425.588788343.59223.29731 9887.1722.74643
9929.23528.303119971.30123.487349992.33313.6335310002.8613.4098510013.3817.05225
10023.9124.6234810034.4325.5165910097.5922.5824210508.2623.3683111119.4427.64108
12653.1248.7095213166.1159.0049513260.3558.17314 13374.8 50.479713479.1554.05877
13500.4957.1626413510.9355.4136313531.8263.41278   13584 65.981113604.8265.00294
13615.2357.6960513625.6555.3776513646.4760.43653 13667.359.5998413730.8266.78733
#Mann= 3 , 0 , 0
5040.879    0.04       05040.879    0.04       013730.82    0.04       0
#XS Ineff= 2 , 0
       07840.723                       0
Bank Sta=5040.879,13730.82
Exp/Cntr=0.3,0.1

Type RM Length L Ch R = 1 ,49951.07,249.253000,249.253000,249.253000
XS GIS Cut Line= 6
447261.614157528724879.098558977446957.203115374723512.534466386
446609.424555451722209.355378032445867.060018927719804.640533715
445205.905746877717767.862762749444824.174627244716520.019033149
#Sta/Elev= 30
5035.12530.651936958.94723.933057414.71223.597057435.48825.370747518.59323.42245
7539.36924.979447570.53423.16102 9881.6922.176659913.09422.823519923.56224.31849
 9934.0328.289869944.49828.721819954.966 25.25299975.90222.899299996.838 13.5024
10007.3114.1879110028.2523.64661 10049.224.1249110080.6122.4183610405.5722.78205
10983.6425.6176711278.2829.15643 11288.827.8905211372.9830.2399512046.3738.63391
12067.3740.3891512445.3546.9724213502.05 63.8413 13648.263.9314913747.2666.22584
#Mann= 3 , 0 , 0
5035.125    0.04       05035.125    0.04       013747.26    0.04       0
#XS Ineff= 2 , 0
       07669.969                       0
Bank Sta=5035.125,13747.26
Exp/Cntr=0.3,0.1

Type RM Length L Ch R = 1 ,49701.81,249.252900,249.252900,249.252900
XS GIS Cut Line= 6
447494.290746987724812.363080472447190.872402608723453.437804222
446841.132765412722144.488493353446067.207864136719599.115311429
445377.303797126717461.338853791445061.005677849716427.346013367
#Sta/Elev= 30
5032.18630.533566063.84225.418057363.574 22.28247509.00724.121147768.70822.61571
 8029.3724.167238112.79522.981999127.27423.432969896.12221.998659932.34925.62702
9974.11823.689929995.00214.8317610005.4413.2020510015.8815.0896710026.3120.85017
10036.7521.70715 10685.823.5766911516.2831.6587411894.8837.6810211979.0237.81417
 12094.741.3298912367.8144.7232212409.7846.4562113174.7355.3634813321.1358.28107
13404.6858.2308913477.7861.1869213509.1160.9441713571.7764.2329613767.7565.50841
#Mann= 3 , 0 , 0
5032.186    0.04       05032.186    0.04       013767.75    0.04       0
#XS Ineff= 2 , 0
       07500.372                       0
Bank Sta=5032.186,13767.75
Exp/Cntr=0.3,0.1

Type RM Length L Ch R = 1 ,49452.56,249.252900,249.252900,249.252900
XS GIS Cut Line= 6
447733.518263996724746.556671843447428.895822734723382.985955149
447022.662809968721880.337840483 446305.93384257719528.437627658
445615.379257679 717391.02035147445291.122684747716337.300228044
#Sta/Elev= 30
5027.38229.869036165.48724.362527342.36122.395667903.69823.559068571.73422.18524
8603.133 23.96398624.06522.435399262.50622.292939314.83724.038149346.23622.02277
9900.21421.491729941.98926.120479962.87625.646079994.20812.5619310025.5218.26397
10035.9624.9738710046.39 25.701710088.1421.3906611115.9126.64026 11831.136.89853
11915.2436.35554 12388.244.5614812587.6546.3497312661.1344.5462912996.4148.20684
13446.3758.8759213467.2762.6234813529.9765.2343213561.3161.7325513788.7966.69302
#Mann= 3 , 0 , 0
5027.382    0.04       05027.382    0.04       013788.79    0.04       0
#XS Ineff= 2 , 0
       07312.785                       0
Bank Sta=5027.382,13788.79
Exp/Cntr=0.3,0.1

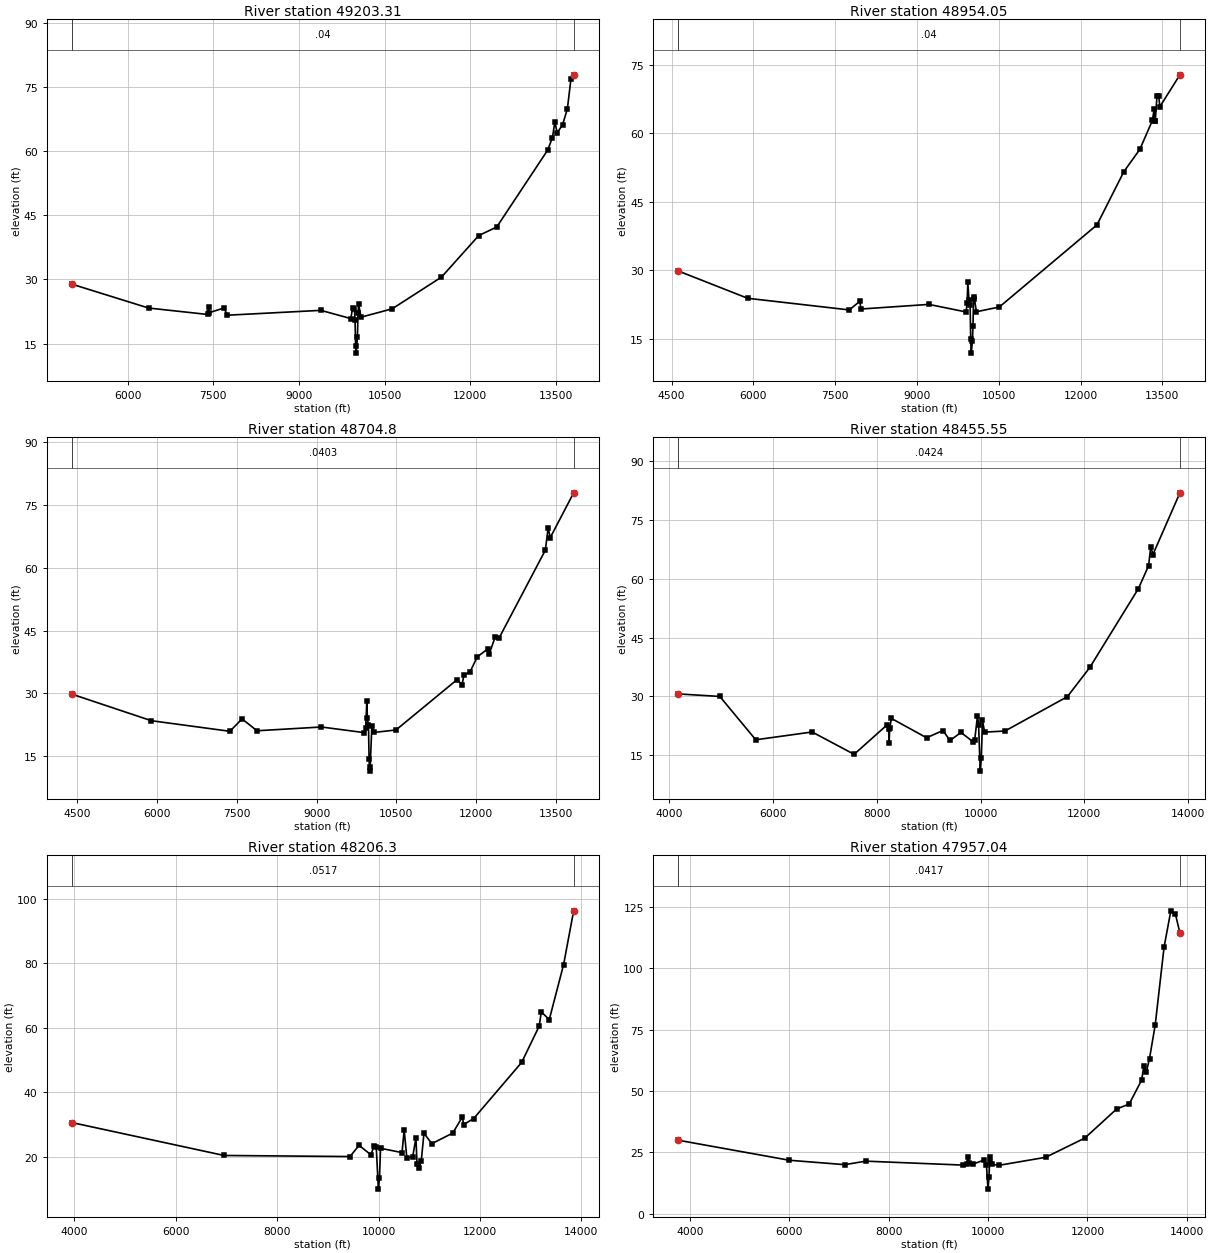
Type RM Length L Ch R = 1 ,49203.31,249.253000,249.253000,249.253000
XS GIS Cut Line= 6
447978.259598643724676.214689434447673.167422742723308.584282666
447267.155333936  721805.8744151446590.648774922719615.749206737
445988.708997279717765.992089555445514.836698294716249.759961888
#Sta/Elev= 30
5023.31128.921356366.64823.340317400.04321.83872  7420.823.619287431.17822.26746
 7690.9723.363897742.99221.658889383.83522.794579907.65420.874319939.084 23.4103
9970.513 23.21579980.98920.531759991.46614.5423410001.9412.80725 10022.9  16.552
10033.3822.1493910043.8624.2303610085.7821.2020410631.5723.1541911494.0230.55894
12146.2840.2586812461.3142.2571713352.34 60.205413436.08 63.146213477.9566.74817
13519.8264.2543813613.9466.1361113697.5269.86718 13760.276.8229513807.4677.79051
#Mann= 3 , 0 , 0
5023.311    0.04       05023.311    0.04       013807.46    0.04       0
#XS Ineff= 2 , 0
       07081.459                       0
Bank Sta=5023.311,13807.46
Exp/Cntr=0.3,0.1

Type RM Length L Ch R = 1 ,48954.05,249.252900,249.252900,249.252900
XS GIS Cut Line= 6
448303.449387759 724995.00293681 447919.45389697723229.711207107
447513.892415255721726.880530253447091.343969911 720357.44235377
446148.382209659717484.041315734445736.329880416716163.088716686
#Sta/Elev= 30
4617.91529.907335895.24723.910927759.85521.363047952.12923.263867972.93721.56125
9217.75522.571989900.85920.916759919.82122.829389932.44327.398189953.50223.62446
 9974.5622.52108 9985.0914.951449995.61911.9086410016.6814.5553410027.2117.86045
10037.74 23.822910047.5324.24906 10090.420.9630510511.6322.0108712301.0739.97498
12794.5251.6296313088.04 56.5167 13318.462.8540613349.8165.3645813360.2862.70112
13370.75 62.790313402.1668.2202613433.5868.1065713454.52 65.835713822.4972.81371
#Mann= 3 , 0 , 0
4617.915    0.04       04617.915    0.04       013822.49    0.04       0
#XS Ineff= 2 , 0
       06844.989                       0
Bank Sta=4617.915,13822.49
Exp/Cntr=0.3,0.1

Type RM Length L Ch R = 1 , 48704.8,249.253000,249.253000,249.253000
XS GIS Cut Line= 6
448588.961229712725133.737564236448245.916581064723495.240544423
447814.157616556721838.363166705447442.883830875720615.374196336
446506.230993509 717809.71372205445959.859070241716075.620772853
#Sta/Elev= 30
4393.12229.841685890.41123.48965 7367.7120.959677596.18523.927887876.89721.08717
9089.68821.98909 9890.2920.648659921.978 21.75169943.10328.082069953.66624.10523
9974.79122.357349985.35414.310019995.91611.4500410006.48 12.457410038.1922.29445
10080.4620.6896110492.6321.2810411641.5833.3024411736.3432.0874611767.9334.37407
11883.7635.1299512020.6438.7214612220.2940.6653812241.3139.3028612356.8943.44455
12430.4543.2157113301.0964.2064713353.3869.4466713395.2267.2356913833.8577.90455
#Mann= 3 , 0 , 0
4393.122  0.0403       04393.122  0.0403       013833.85  0.0403       0
#XS Ineff= 2 , 0
       06607.817                       0
Bank Sta=4393.122,13833.85
Exp/Cntr=0.3,0.1

Type RM Length L Ch R = 1 ,48455.55,249.252900,249.252900,249.252900
XS GIS Cut Line= 6
448871.123724133725270.844691813448486.820832014723410.438041553
448056.348751634 721753.23186855447658.488541692  720448.9091115
446842.450321823718060.768679306446184.990231246715987.525970697
#Sta/Elev= 30
4167.45130.658154972.72330.008825665.54118.943446752.13220.935537561.90215.23193
8205.02722.846238225.91721.821928236.36218.186358246.80721.874628280.27624.39732
8958.49519.461279273.73221.301139410.53318.773329621.80420.810549854.84718.43556
9886.73219.006649939.87525.057259961.13322.761929993.01810.9440810014.2914.34616
10035.5523.8998710078.0920.9010310470.46 21.185111673.2429.9581312104.5137.40057
13039.1957.4817513238.1863.3639413280.0868.2608913321.9766.2421413842.2381.99096
#Mann= 3 , 0 , 0
4167.451  0.0424       04167.451  0.0424       013842.23  0.0424       0
#XS Ineff= 2 , 0
       0 6370.13                       0
Bank Sta=4167.451,13842.23
Exp/Cntr=0.3,0.1

Type RM Length L Ch R = 1 , 48206.3,249.252900,249.252900,249.252900
XS GIS Cut Line= 6
449137.141804725725400.106998593 448714.53802231723326.159072682
448285.616270125721668.558360666 447914.34522444720445.573462859
447027.938507915717813.476246044446421.077267617715895.144086927
#Sta/Elev= 30
3950.56130.552226954.022 20.3268 9436.9419.995449616.30423.471229849.57520.53728
9912.20423.39765 9954.6122.977229997.0179.88046610018.2513.3043610039.4822.56027
10462.8921.2146110505.1128.1849210557.8919.5619710673.9919.9839210737.3225.74796
10758.43 17.677610800.64 16.374610842.8618.7633610895.6427.2256911050.6123.98674
11463.4527.2852111654.4832.3219211675.5529.9078611875.6431.7838112821.3849.20476
13167.3960.4752513209.3364.8983513366.3162.50339 13648.779.5767213847.2796.26982
#Mann= 3 , 0 , 0
3950.561  0.0517       03950.561  0.0517       013847.27  0.0517       0
#XS Ineff= 2 , 0
       06141.634        10858.12       0
Bank Sta=3950.561,13847.27
Exp/Cntr=0.3,0.1

Type RM Length L Ch R = 1 ,47957.04,249.253000,249.253000,249.253000
XS GIS Cut Line= 6
449375.733668923725516.042481914449021.999850333 723637.16525735
448777.884481698 722589.73458159448510.596245348721595.045747951
448090.936242044720216.048145398446665.251164407715799.597779468
#Sta/Elev= 30
3762.04329.949686004.02521.767497116.00119.98162 7540.9521.405049505.90819.79666
 9568.9520.17856 9600.4723.145499621.48420.768599695.03320.171719926.18421.91535
9968.21220.026039999.73310.0146910020.7614.8664210031.2821.1752310041.7923.23672
10083.8520.0907310220.5319.7140111158.1522.96871 11947.930.7981512589.2142.66187
12841.0344.6647813092.6654.48238 13134.660.0267313187.0257.8634113249.9163.19914
13364.95 76.920513542.73108.525613678.69123.360113772.81121.912413862.12 114.312
#Mann= 3 , 0 , 0
3762.043  0.0417       03762.043  0.0417       013862.12  0.0417       0
#XS Ineff= 2 , 0
       05931.255        10938.08       0
Bank Sta=3762.043,13862.12
Exp/Cntr=0.3,0.1

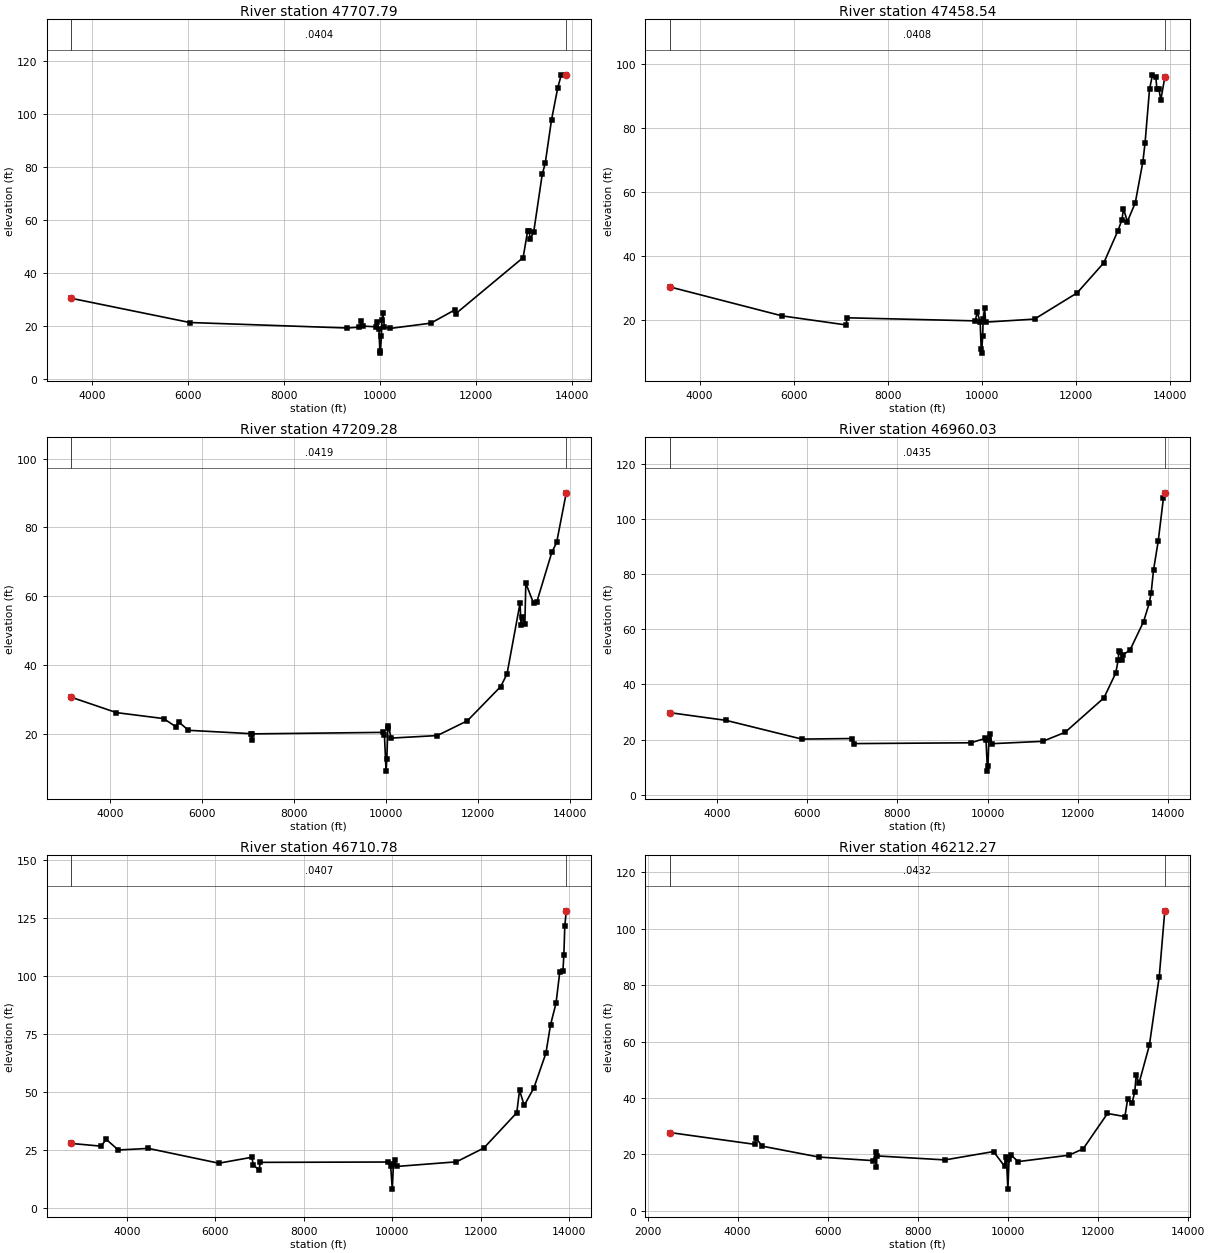
Type RM Length L Ch R = 1 ,47707.79,249.252900,249.252900,249.252900
XS GIS Cut Line= 6
  449629.3940458 725639.29998897449423.178863913724456.769659311
449247.908123642723565.626487523448865.002895772721971.670362994
448400.406709164720388.457682297446905.108896077  715705.7404062
#Sta/Elev= 30
3565.44630.467966032.958 21.35399302.85819.287389565.03719.593999606.98521.82786
9638.44720.014519921.26719.717639931.73621.547799973.61319.031539994.55110.68384
10005.029.81510810025.9716.2191610036.4422.3861110057.3924.8261710088.8219.60146
10214.5119.1362111056.0821.1068411551.1326.05334 11572.224.6231512980.3345.81396
13074.6855.8789213106.1455.72874 13127.152.8064513200.4955.4386513378.3277.17601
13441.0681.3824113571.8297.6995613702.47109.855713775.67114.697413879.46114.6322
#Mann= 3 , 0 , 0
3565.446  0.0404       03565.446  0.0404       013879.46  0.0404       0
#XS Ineff= 2 , 0
       05721.234        11019.44       0
Bank Sta=3565.446,13879.46
Exp/Cntr=0.3,0.1

Type RM Length L Ch R = 1 ,47458.54,249.252900,249.252900,249.252900
XS GIS Cut Line= 6
449886.091372102725764.033196837449651.340247244724385.911470965
449479.401961535723494.119923353449101.077552587721899.081445009
448739.816762537720642.669260547447139.322234303715614.091708645
#Sta/Elev= 30
3367.85430.261465754.99221.206997121.37418.366277131.71120.614929865.42919.64849
9907.34222.486459970.21219.149899991.16910.8772710001.649.56248810022.5915.06741
10033.0720.1883510064.4923.7564110085.4419.2542811126.4420.2017412031.8128.38899
12599.2737.7652712903.3847.9050912987.2351.3112413018.6854.7149713102.53 50.7069
13270.0956.5545713432.3769.4539413479.1775.4191213573.2692.0530813635.9996.58489
13706.7795.8842113730.0892.2970813771.8992.1518313813.7188.7369113898.2595.80546
#Mann= 3 , 0 , 0
3367.854  0.0408       03367.854  0.0408       013898.25  0.0408       0
#XS Ineff= 2 , 0
       05576.374        11100.68       0
Bank Sta=3367.854,13898.25
Exp/Cntr=0.3,0.1

Type RM Length L Ch R = 1 ,47209.28,249.253000,249.253000,249.253000
XS GIS Cut Line= 6
450145.850066632725890.253970936449716.196133733723419.102455899
449343.284671575721822.802922338448913.409654915720337.317000419
447739.325864702716733.736908734447367.643474132715524.748614803
#Sta/Elev= 30
3165.67530.653384144.09126.204975168.90924.471765433.667 22.12125494.81123.51602
5708.91421.066587063.36520.092747084.02518.343337094.35520.028379944.01720.46755
9965.03619.73052   100019.21227310017.6712.8171510038.73 21.615910049.2622.42766
10112.4518.80621 11112.919.5410111765.8323.8230612491.2733.7781812627.8337.43466
12910.8357.9626412931.7951.7390212963.2353.8355813015.6251.9961413036.5863.76521
13204.2357.9821913277.3958.4476213601.3772.7626313705.8875.6223613915.0290.03507
#Mann= 3 , 0 , 0
3165.675  0.0419       03165.675  0.0419       013915.02  0.0419       0
#XS Ineff= 2 , 0
       05537.626        11178.35       0
Bank Sta=3165.675,13915.02
Exp/Cntr=0.3,0.1

Type RM Length L Ch R = 1 ,46960.03,249.252900,249.252900,249.252900
XS GIS Cut Line= 6
450401.424918532726016.383971676450032.144038916723763.508754194
449583.883755684721741.060946167449155.882811219 720255.05175209
448106.952304602717086.197534442447596.409137845 715435.23161599
#Sta/Elev= 30
2958.58929.737634205.77226.940155882.07420.166036999.93420.371047041.11918.53364
9627.031 18.83129943.61520.387939964.74719.682599996.4458.55807110007.0110.40974
10028.1520.2277810051.6222.1319310091.5418.49866 11220.419.3581111715.4422.60798
12577.1135.0977912839.4144.1072512891.8748.6988212912.85 52.234412944.2451.89561
12975.6248.7116412996.5450.7155113153.4652.3633313456.8262.7697513582.1969.45361
13623.9573.1192913676.1381.4029613780.5191.8869413895.26 107.41513926.28109.4077
#Mann= 3 , 0 , 0
2958.589  0.0435       02958.589  0.0435       013926.28  0.0435       0
#XS Ineff= 2 , 0
       05497.709        11250.25       0
Bank Sta=2958.589,13926.28
Exp/Cntr=0.3,0.1

Type RM Length L Ch R = 1 ,46710.78,498.505900,498.505900,498.505900
XS GIS Cut Line= 6
450647.970016539726154.544509709450257.002749205723684.349593297
449817.509566098721660.006972522449391.663404077720173.399123535
448341.812491149717002.918058664447832.005827725715343.041606888
#Sta/Elev= 30
2740.58527.99135 3408.0426.832073529.47929.728013802.27225.171514480.75325.86074
6076.14219.48979 6824.2322.052326855.09118.850956988.82216.378787009.39619.85442
9910.31319.999789963.10718.31075   100018.33341210026.4719.3066510058.1520.71173
 10100.418.0970111450.8120.0797412071.55 26.019812816.5441.2097612879.4650.94752
12984.1144.3326113203.6651.8914313475.4866.8113113579.8778.9958113705.03 88.3871
13788.48101.625513861.48102.415213882.31109.294213903.14121.506613936.41128.1139
#Mann= 3 , 0 , 0
2740.585  0.0407       02740.585  0.0407       013936.41  0.0407       0
#XS Ineff= 2 , 0
       05468.294        11322.54       0
Bank Sta=2740.585,13936.41
Exp/Cntr=0.3,0.1

Type RM Length L Ch R = 1 ,46212.27,64.972900,64.972900,64.972900
XS GIS Cut Line= 6
450903.900906801726297.964718714450020.856785893720939.979853705
449699.740230531719609.639838696 449430.76602301718669.671552703
449077.728434622717182.434846476448596.298944056715576.914860278
#Sta/Elev= 30
2497.47527.724794385.11323.538064405.37825.766124547.23222.898295803.65519.03583
7009.30517.769647059.95920.892387080.22115.649877090.35219.448488600.86618.02355
9678.59620.988629926.01315.743019946.51218.95527 9967.0117.880159997.7587.664847
10023.94 18.362810059.6319.8181710227.4917.4282511350.3319.6890611667.9321.94747
12208.2334.49594 12594.5 33.389112657.1439.68941 12751.138.0828812813.74 42.1717
12845.0648.12663 12907.745.2322613137.38 58.669713356.6283.00428 13479.9106.3692
#Mann= 3 , 0 , 0
2497.475  0.0432       02497.475  0.0432       0 13479.9  0.0432       0
#XS Ineff= 2 , 0
       05274.056         11514.1       0
Bank Sta=2497.475,13479.9
Exp/Cntr=0.3,0.1

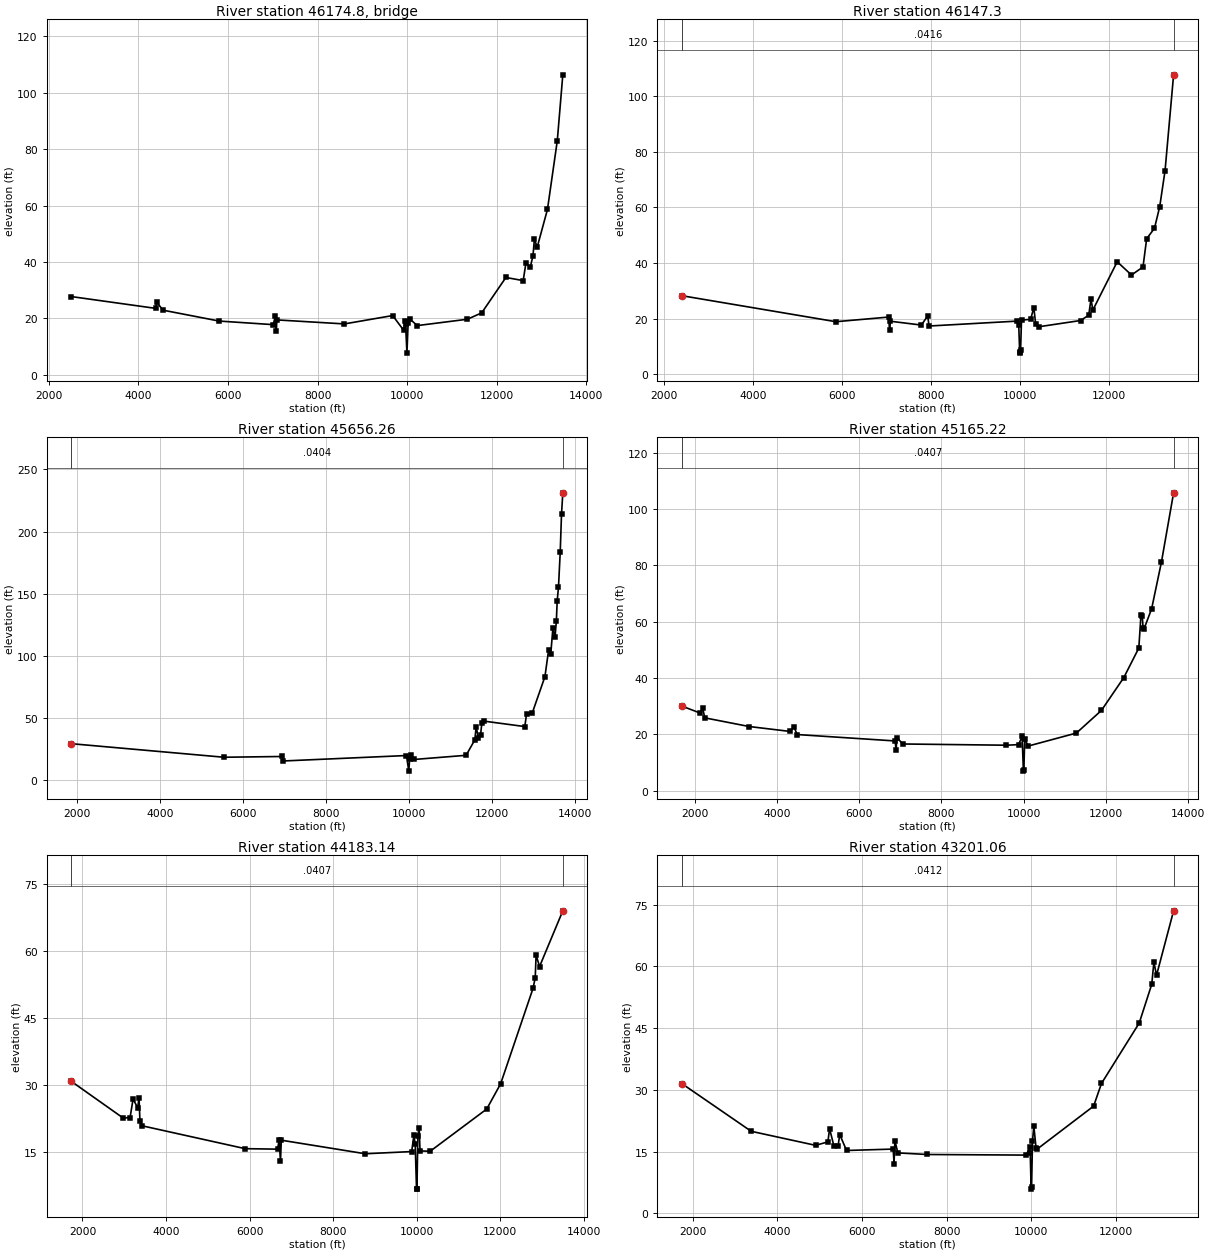
Type RM Length L Ch R = 3 , 46174.8,,,
BEGIN DESCRIPTION:
END DESCRIPTION:
Bridge Culvert--1,0,-1,-1, 0
Deck Dist Width WeirC Skew NumUp NumDn MinLoCord MaxHiCord MaxSubmerge Is_Ogee
24.986450,15.000000,2.6,0, 13, 13, , , 0.95, 0, 0,0,,
 9937.84 9944.33 9954.66 9962.31 9969.50 9969.5010019.5010019.5010024.1510027.31
10036.9010037.8010040.60
   18.64   18.79   19.02   19.15   19.21   19.21   19.60   19.60   19.64   19.85
   19.58   19.56   19.52
 -981.36 -981.21 -980.98 -980.85 -980.79   16.21   16.60 -980.40 -980.36 -980.15
 -980.42 -980.44 -980.48
 9937.84 9944.33 9954.66 9962.31 9969.59 9969.5910019.5910019.5910024.1510027.31
10036.9010037.8010040.60
   18.64   18.79   19.02   19.15   19.21   19.21   19.60   19.60   19.64   19.85
   19.58   19.56   19.52
 -981.36 -981.21 -980.98 -980.85 -980.79   16.21   16.60 -980.40 -980.36 -980.15
 -980.42 -980.44 -980.48
BR Coef=-1 , 0 , 0 ,, 0 ,,,0.8,0,1,0,
WSPro=,,,, 1 ,,,, 0 ,,,, 0 ,,,,-1 ,-1 ,-1 , 0 , 0 , 0 , 0 , 0
BC Design=,, 0 ,, 0 ,,,,,,

Type RM Length L Ch R = 1 , 46147.3,491.040600,491.040600,491.040600
XS GIS Cut Line= 6
451025.680294603726366.208240405450236.923944086721593.407915816
450091.090610713720902.001665816449564.829150826718884.539654508
449206.749570757717362.701439261448735.831652999715569.327664137
#Sta/Elev= 30
2398.97128.256255855.91918.921517042.20620.583997062.48915.924127082.77319.08479
7777.31417.712577919.85720.993727950.58117.36963 9935.5419.137559966.50217.61933
9987.1448.0103759997.4657.62477810007.798.69373510028.4319.4804510233.5619.79797
10305.3524.0128710346.3818.0832610418.2917.1059511354.7819.3473911538.9521.23304
11590.1127.0522711631.4423.1038612179.4140.4648412499.9235.7084312758.3938.58972
12841.1148.75123 13016.852.5050213134.9260.3046413254.6773.2452913446.63107.6639
#Mann= 3 , 0 , 0
2398.971  0.0416       02398.971  0.0416       013446.63  0.0416       0
#XS Ineff= 2 , 0
       05188.662        11542.97       0
Bank Sta=2398.971,13446.63
Exp/Cntr=0.3,0.1

Type RM Length L Ch R = 1 ,45656.26,491.040600,491.040600,491.040600
XS GIS Cut Line= 6
451646.947729021726714.358107015451119.581971228722941.499413565
450800.469212383721333.689537436450425.122017622719951.311604992
449467.753927529717050.235342279448916.680896878715214.931252867
#Sta/Elev= 30
1864.46129.268075549.06718.352556953.34218.962786963.57315.329999947.65319.73236
10003.957.17891610025.0717.3394410056.7419.89726 10141.216.5955411386.03 19.9114
11596.53 32.393411628.07 42.954911680.6334.0492111733.1935.9830811764.7345.54932
11817.26 47.430212801.48 43.046212843.2653.1907312978.7253.7581613286.4883.21097
13374.54104.494613426.62101.284813478.62 122.23813530.57115.010613561.74127.8185
13582.51144.423713613.68155.371613655.24183.471613686.41214.018313717.65231.2107
#Mann= 3 , 0 , 0
1864.461  0.0404       01864.461  0.0404       013717.65  0.0404       0
#XS Ineff= 2 , 0
       04542.167                       0
Bank Sta=1864.461,13717.65
Exp/Cntr=0.3,0.1

Type RM Length L Ch R = 1 ,45165.22,982.081100,982.081100,982.081100
XS GIS Cut Line= 6
 452411.55779016726670.566080064451661.899264991723689.839988351
451425.640778273722048.124528438451097.390996963720526.812782571
449881.262375772716729.999384567449415.530919343715120.353739336
#Sta/Elev= 30
1692.275 30.04342131.09427.609572192.962 29.39522244.51925.897473327.21822.80575
4327.426 21.05554409.91722.772984492.40819.963856875.58317.686746895.97514.33674
6916.36818.887357059.15716.615599581.00516.175639876.80716.386639961.372 19.3376
9993.0846.97822610003.667.22315910024.8118.3884610109.4115.8811411281.3120.49489
11890.4628.5368212434.2940.1952212798.9350.6705512850.9662.2997512882.1862.02987
12902.9957.7856212923.8157.3808313111.12 64.633813349.8681.2525113644.87105.7741
#Mann= 3 , 0 , 0
1692.275  0.0407       01692.275  0.0407       013644.87  0.0407       0
#XS Ineff= 2 , 0
       0 4257.02                       0
Bank Sta=1692.275,13644.87
Exp/Cntr=0.3,0.1

Type RM Length L Ch R = 1 ,44183.14,982.081200,982.081200,982.081200
XS GIS Cut Line= 6
452993.608228147726386.881529421452405.985738754723409.179424495
452245.036146075721758.316126242451988.698391795 720223.35947369
450847.705817044716445.516753778450449.032975197 714924.41097036
#Sta/Elev= 30
1730.70230.893262965.95622.736053139.23422.747283210.58426.919583322.70624.98061
3353.28427.234853376.34621.947423424.63420.952795895.11915.835886670.13615.72616
6710.48817.799066740.75112.977916760.95117.727098773.14514.695869883.08415.18629
9935.71818.830319967.29816.854949998.8786.83946110009.416.79051610030.4918.65288
 10062.120.5602210083.1815.3310110325.5415.2533511679.8224.6922312013.3630.34477
12790.1551.70769 12841.854.0461612862.4659.10477 12945.156.5423313502.05 68.9993
#Mann= 3 , 0 , 0
1730.702  0.0407       01730.702  0.0407       013502.05  0.0407       0
#XS Ineff= 2 , 0
       0 3695.56                       0
Bank Sta=1730.702,13502.05
Exp/Cntr=0.3,0.1

Type RM Length L Ch R = 1 ,43201.06,982.081100,982.081100,982.081100
XS GIS Cut Line= 6
453419.953410298 726129.46557036453043.820969969722650.394930676
452791.201505244719583.346217126452600.787263811718714.814423949
451946.710601479716619.160717562 451534.92913717714718.534746349
#Sta/Elev= 30
1752.90531.497983386.83619.941214905.63616.531575197.32517.366645237.55920.57613
5337.71816.447315437.80616.400245477.84119.148875637.98115.278366739.758 15.6216
 6759.8112.090386779.86917.641516850.07514.69121 7542.8414.306479881.48514.15789
9966.01716.076619976.58314.591419997.7165.89108310008.286.501338 10029.417.51587
10061.07 21.219210113.8715.8398410145.5415.6616611472.89 26.053811658.5331.55911
12550.4446.2465312846.2555.6723712897.2161.0790512958.3557.8183613362.1473.50683
#Mann= 3 , 0 , 0
1752.905  0.0412       01752.905  0.0412       013362.14  0.0412       0
#XS Ineff= 2 , 0
       03143.639                       0
Bank Sta=1752.905,13362.14
Exp/Cntr=0.3,0.1