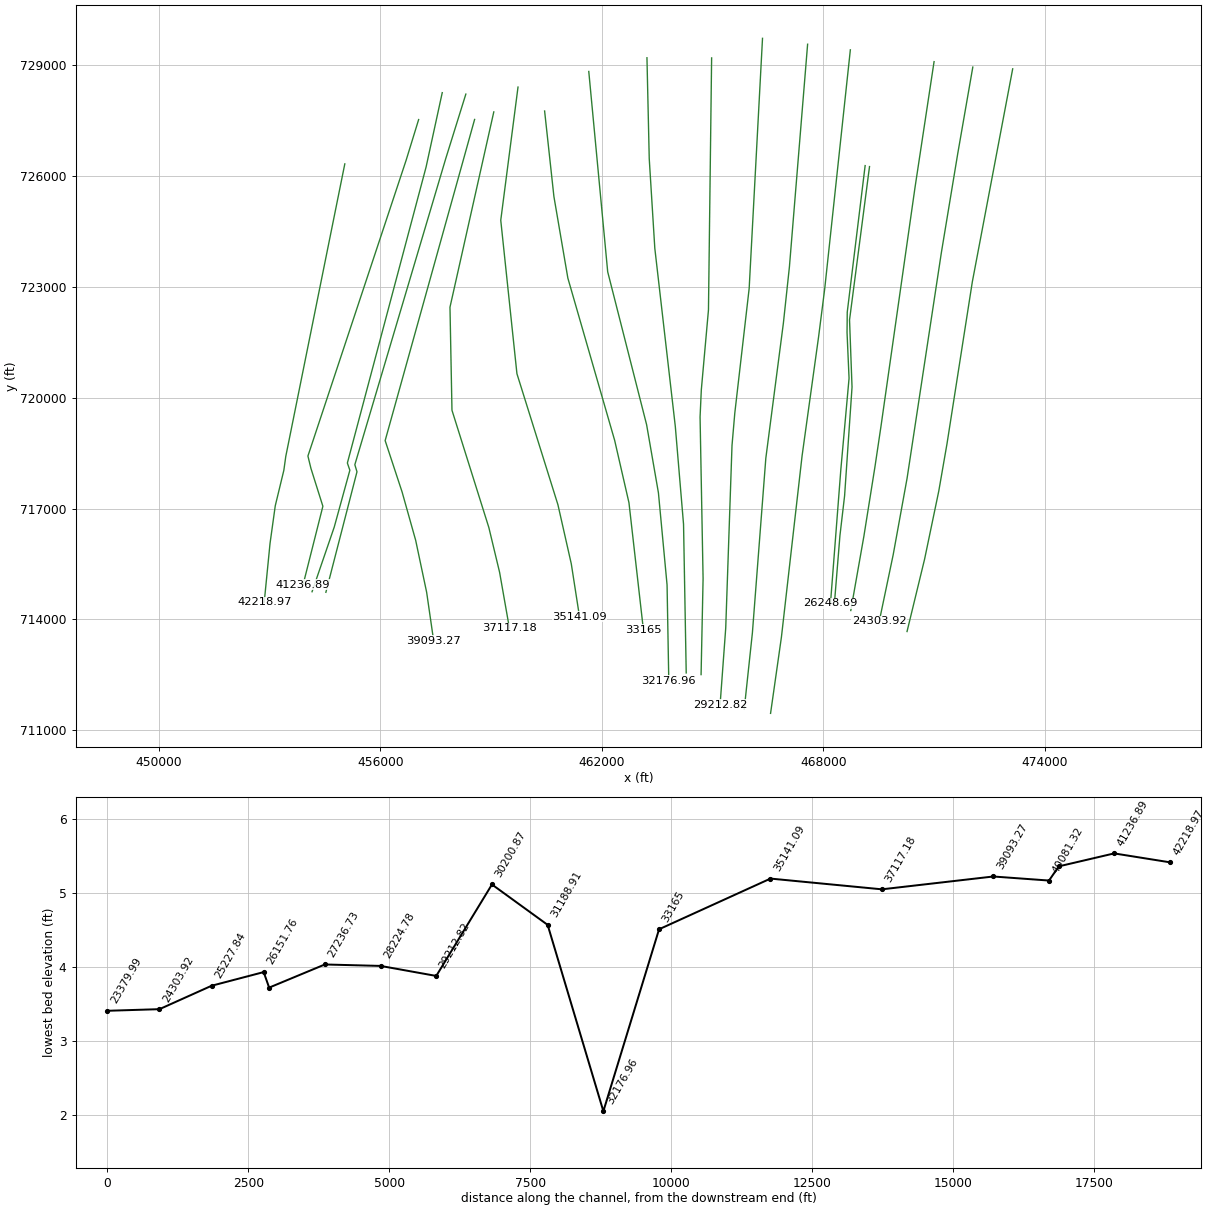
HEC-RAS study 691_ras.prj: 691

--- 691_ras.g01 (geometry) --- (continued)

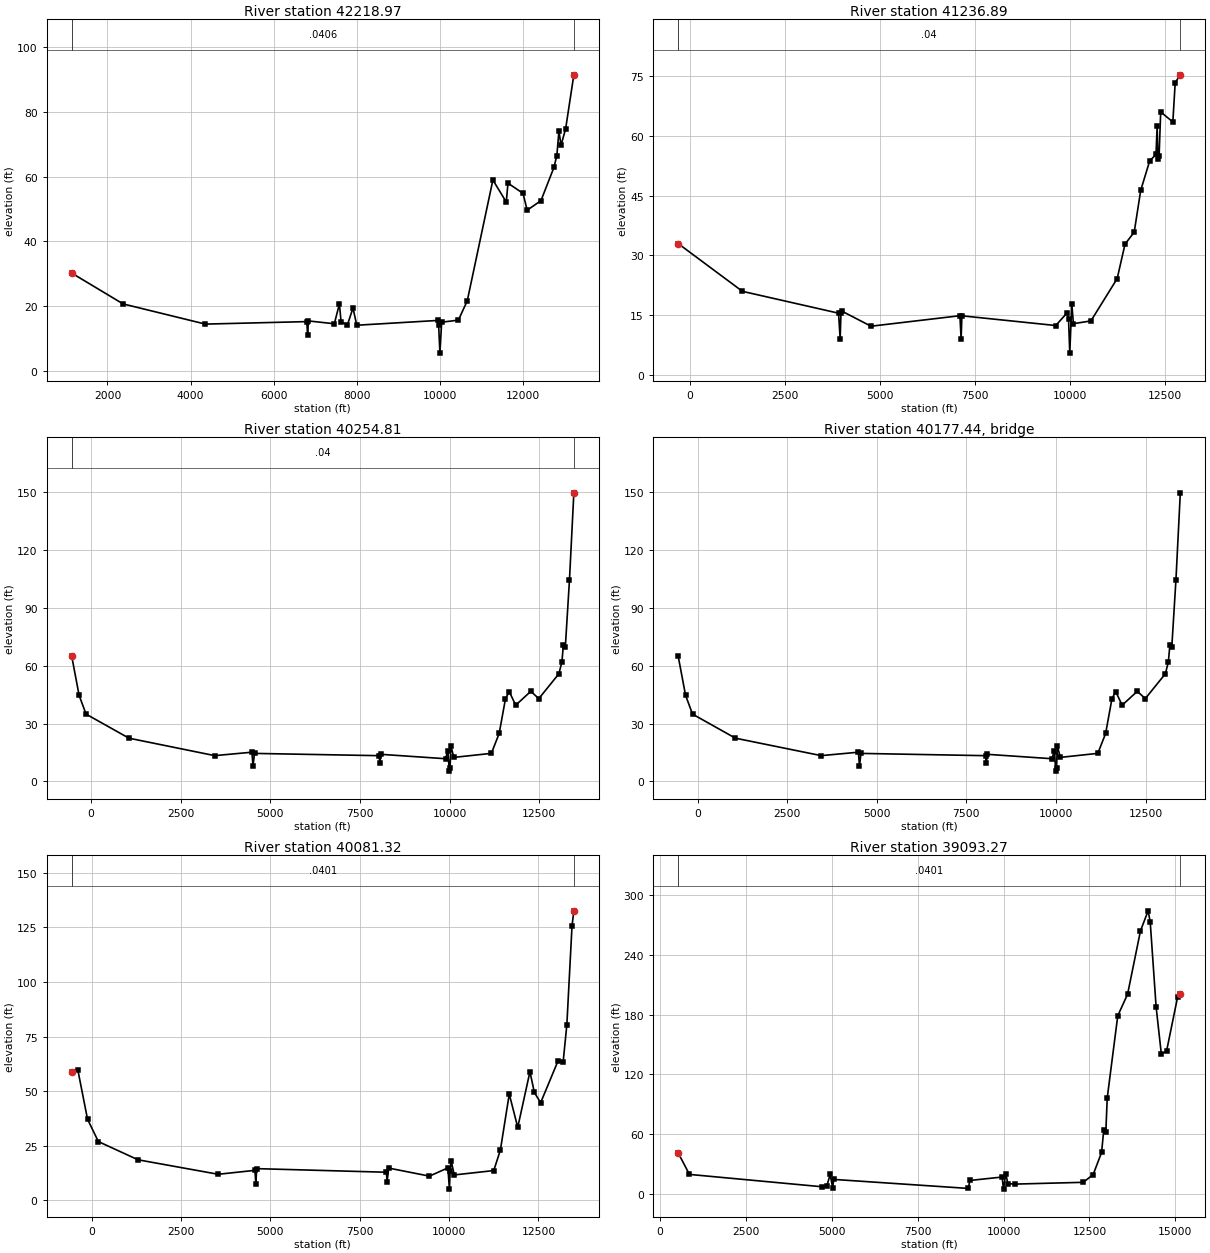
Type RM Length L Ch R = 1 ,42218.97,982.081200,982.081200,982.081200
XS GIS Cut Line= 6
455039.640801877726335.549765915453441.200088441718414.661737487
453389.042295456718039.682640135453156.740505636717078.939028755
453014.692150652716057.326954558 452857.61533463714467.765244231
#Sta/Elev= 30
 1140.5830.148492375.53220.62515 4354.6414.387986792.81915.159566813.22211.01294
6833.62515.368367455.92214.493397578.34120.586347619.147 15.06367772.17114.18912
7904.79219.363337996.60614.040159944.42515.517499965.23314.073149996.4455.414338
10037.9814.9855710439.9215.6046310653.62 21.574411270.2358.93579 11592.552.11848
11632.7757.9607611994.76 54.814412095.3249.5893512426.9352.5672812738.3562.80208
12808.6666.4957212858.8874.07961 12909.169.6818613019.5974.72177 13217.791.45217
#Mann= 3 , 0 , 0
 1140.58  0.0406       0 1140.58  0.0406       0 13217.7  0.0406       0
#XS Ineff= 2 , 0
       0                               0
Bank Sta=1140.58,13217.7
Exp/Cntr=0.3,0.1

Type RM Length L Ch R = 1 ,41236.89,982.081100,982.081100,982.081100
XS GIS Cut Line= 6
457039.070702225727535.825508088456700.094833046726434.202072978
454040.717228681718424.599920616454122.421816498718090.272969112
454445.690346986717064.827897251453908.447390914 714934.50650242
#Sta/Elev= 30
-300.265 32.96921388.86721.013753917.69715.540533959.8449.0791143980.918 15.7004
4001.99116.071784771.17712.275197110.34514.905777141.9559.0983247163.02914.88081
9631.23812.450849937.01815.688379968.88313.9609310000.775.53352610053.9217.95067
10096.4512.9114310557.0613.6033511248.0924.2138311454.3632.8445311696.2835.85476
11866.8846.3053612104.0853.7211312269.0955.3036412300.0362.4580612320.6554.11906
12350.5954.8603812392.85 65.963512712.5563.4545112774.4373.3036612909.0175.26425
#Mann= 3 , 0 , 0
-300.265    0.04       0-300.265    0.04       012909.01    0.04       0
#XS Ineff= 2 , 0
       0                               0
Bank Sta=-300.265,12909.01
Exp/Cntr=0.3,0.1

Type RM Length L Ch R = 1 ,40254.81,173.495100,173.495100,173.495100
XS GIS Cut Line= 6
457678.151184112 728264.60149622457240.543575913726250.658826828
455109.218585968718235.506021738455176.339078814718039.859768093
454753.572118044  716501.3250615454152.589277208714749.892324433
#Sta/Elev= 30
-540.375 64.7368-336.11544.62472-141.68234.87571 1055.6222.411823448.886 13.3805
4485.80615.154924516.8498.1157644558.23914.534058035.00113.358278055.6969.569725
8086.73914.05263 9888.7911.779389952.223 16.02059994.5125.35882910015.667.184343
 10036.518.4578110119.4612.46699 11166.914.5565811384.6924.8667811560.9942.83301
11665.6346.5554111845.3639.4846512268.2546.6918912490.2742.88256 13050.655.74762
13135.1861.8830813177.4770.8061713230.3369.5039713346.63104.453413468.33149.4404
#Mann= 3 , 0 , 0
-540.375    0.04       0-540.375    0.04       013468.33    0.04       0
#XS Ineff= 2 , 0
       0                               0
Bank Sta=-540.375,13468.33
Exp/Cntr=0.3,0.1

Type RM Length L Ch R = 3 ,40177.44,,,
BEGIN DESCRIPTION:
END DESCRIPTION:
Bridge Culvert--1,0,-1,-1, 0
Deck Dist Width WeirC Skew NumUp NumDn MinLoCord MaxHiCord MaxSubmerge Is_Ogee
79.247550,15.000000,2.6,0, 9, 9, , , 0.95, 0, 0,0,,
 9949.45 9956.25 9971.69 9971.6910021.6910021.6910035.5110040.3110042.76
   14.42   14.50   14.43   14.43   14.21   14.21   14.15   14.19   14.18
 -985.58 -985.50 -985.57   11.43   11.21 -985.79 -985.85 -985.81 -985.82
 9949.45 9956.25 9974.87 9974.8710024.8710024.8710035.5110040.3110042.76
   14.42   14.50   14.42   14.42   14.19   14.19   14.15   14.19   14.18
 -985.58 -985.50 -985.58   11.42   11.19 -985.81 -985.85 -985.81 -985.82
BR Coef=-1 , 0 , 0 ,, 0 ,,,0.8,0,1,0,
WSPro=,,,, 1 ,,,, 0 ,,,, 0 ,,,,-1 ,-1 ,-1 , 0 , 0 , 0 , 0 , 0
BC Design=,, 0 ,, 0 ,,,,,,

Type RM Length L Ch R = 1 ,40081.32,988.044900,988.044900,988.044900
XS GIS Cut Line= 5
458317.231666058728225.359712258457773.244020522726480.300453857
 455311.30696705718190.168856651455369.293484718717998.218968824
454527.492057115714735.422737271
#Sta/Elev= 30
-555.63758.86577-387.66659.86806-115.32637.19563188.437426.933351298.63818.59281
3541.44211.964784567.98713.764864595.0387.4951894615.90114.546528246.11412.89775
8266.9778.5283928308.70414.810729450.59811.116269967.40214.9020610009.195.167478
10030.0813.5126210061.4217.9155210144.7111.6605511249.7513.6641811435.6523.08275
11683.5148.6706611921.0433.4489812261.8458.9211812385.7749.4246412561.3444.71605
13046.7363.8143513191.3163.4709613294.5980.4228113439.17125.603813490.37 132.562
#Mann= 3 , 0 , 0
-555.637  0.0401       0-555.637  0.0401       013490.37  0.0401       0
#XS Ineff= 2 , 0
       0                               0
Bank Sta=-555.637,13490.37
Exp/Cntr=0.3,0.1

Type RM Length L Ch R = 1 ,39093.27,1976.089800,1976.089800,1976.089800
XS GIS Cut Line= 6
458554.280724257727538.673169091456132.099990606718843.074456468
456591.640690923717448.807735801456958.687711209716142.031522185
457255.920656234714734.052076444457444.927331656713427.083704412
#Sta/Elev= 30
533.159941.35489859.167919.949334725.4537.5682964860.5658.5393334954.10419.96938
5026.857 6.745365058.03714.948058977.4065.9149599018.87113.882639958.622 17.3141
10000.815.22215110064.0920.8075110127.3810.7375410327.7510.2529412320.5712.03285
12608.7919.7673512855.0341.9641912916.4764.3771412977.8462.3362813018.7696.56822
13325.15178.746213610.31200.258713986.05263.737914209.07283.783314269.73272.6012
14441.58187.543214593.21140.379614744.53143.238515067.14197.570815145.55200.7386
#Mann= 3 , 0 , 0
533.1599  0.0401       0533.1599  0.0401       015145.55  0.0401       0
#XS Ineff= 2 , 0
       0                               0
Bank Sta=533.1599,15145.55
Exp/Cntr=0.3,0.1

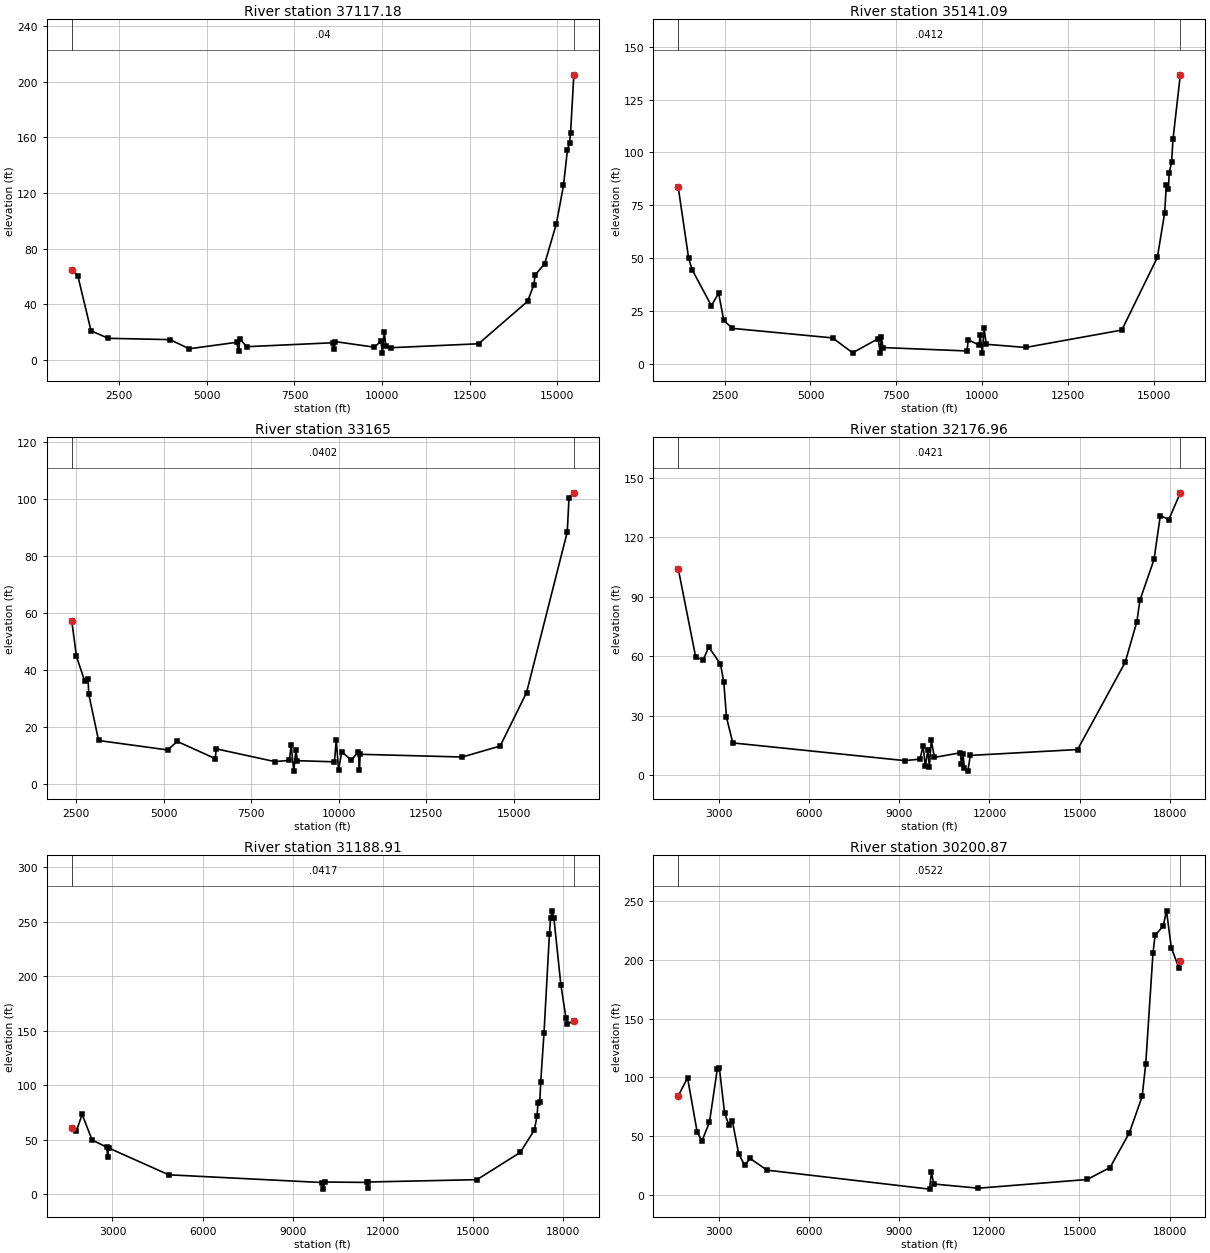
Type RM Length L Ch R = 1 ,37117.18,1976.089800,1976.089800,1976.089800
XS GIS Cut Line= 6
459074.037499905727743.246366262  457887.6140576722455.339835763
457941.593842655719664.753053308458940.156000555  716488.2858565
459231.141347557715276.548350602 459497.09379828713762.609020233
#Sta/Elev= 30
1145.534  65.025  1317.260.705361695.05121.048342187.20915.691513951.23314.74182
4494.4658.1627845847.63512.813315909.1556.4626035939.91415.358856134.727 9.66524
8595.73712.50183 8615.747.6704188645.74613.383499777.5449.3196849967.29913.58432
10009.475.049137 10062.220.0758110104.3810.3557510241.488.92578512751.8511.77089
14148.6342.2046714332.2854.2801714362.7961.1285114637.3269.2241814972.1197.99104
15174.75125.530315286.03150.780115346.62156.009115376.91163.465115470.21204.9496
#Mann= 3 , 0 , 0
1145.534    0.04       01145.534    0.04       015470.21    0.04       0
#XS Ineff= 2 , 0
       0                               0
Bank Sta=1145.534,15470.21
Exp/Cntr=0.3,0.1

Type RM Length L Ch R = 1 ,35141.09,1976.089900,1976.089900,1976.089900
XS GIS Cut Line= 6
459729.935889214728415.962662995  459262.6140576724809.506502435
459700.752970904 720653.38770467460811.528479338717103.065837979
461172.857650489715504.224575594461395.153342873714072.938147321
#Sta/Elev= 30
1148.85483.529591451.09750.128751551.52244.695962113.90327.588852324.796 33.4625
2476.40720.619492729.11316.885975645.88312.381576229.0975.3605686973.19812.01563
7033.5315.3443627063.69712.736767113.9747.8228999563.5546.213318 9595.1511.49783
9911.1119.0327779942.70713.59306 10005.9   5.19410058.5916.8383910121.82 9.36876
11268.037.87852214070.3216.0932915106.1450.4322615318.47 71.445515368.9284.80474
15429.4782.9282815449.6590.3313415520.2995.3444915560.66106.134115774.61136.6826
#Mann= 3 , 0 , 0
1148.854  0.0412       01148.854  0.0412       015774.61  0.0412       0
#XS Ineff= 2 , 0
       0                               0
Bank Sta=1148.854,15774.61
Exp/Cntr=0.3,0.1

Type RM Length L Ch R = 1 ,   33165,988.044900,988.044900,988.044900
XS GIS Cut Line= 6
  460450.1140576727767.839835778460702.100942105725450.856955543
461079.839072287723241.831690714462346.570294142718850.179767802
462734.076499313717161.098203391463125.745595157713716.832191259
#Sta/Elev= 30
2371.46457.21446 2504.9844.790592736.15136.29163 2836.6636.804262856.76231.53977
3138.18815.257575112.07711.940295385.18514.932426471.3068.909324 6501.8712.32196
8174.6227.8520138589.7248.2694088641.728 13.64878714.5334.5104858776.93712.09059
8818.7118.1801379877.6437.7740759930.18115.410659995.5275.00113510087.8411.30655
10361.188.36396210560.9311.3687610592.46 4.8057410613.4410.4201413530.789.461796
 14612.6 13.313715367.38 32.045716530.95 88.408716581.02100.410716719.38102.1626
#Mann= 3 , 0 , 0
2371.464  0.0402       02371.464  0.0402       016719.38  0.0402       0
#XS Ineff= 2 , 0
       0                               0
Bank Sta=2371.464,16719.38
Exp/Cntr=0.3,0.1

Type RM Length L Ch R = 1 ,32176.96,988.044900,988.044900,988.044900
XS GIS Cut Line= 6
461646.080173473728838.211713439462158.509490171723412.755989511
 463212.36505748719271.983521612463532.080368253717428.801510724
463766.125161766714933.204413205463812.585842197712340.383037781
#Sta/Elev= 30
 1648.64104.12852232.32859.374152482.61758.273962662.82464.635083053.53256.07739
3163.74147.041493253.91129.126193464.41316.28595 9178.297.3673719689.7448.088518
9794.58614.701959867.975  4.44659951.693 12.632610003.784.18936510066.3517.72178
10171.048.97773611036.4211.3059411067.335.43325511118.8310.7016111170.33 3.62756
11283.552.05641211365.689.98384314933.6712.9395716516.4556.9222516906.6377.45479
17006.6688.1613217476.69 108.811 17686.7130.959617966.72128.896418351.36 142.422
#Mann= 3 , 0 , 0
 1648.64  0.0421       0 1648.64  0.0421       018351.36  0.0421       0
#XS Ineff= 2 , 0
       0                               0
Bank Sta=1648.64,18351.36
Exp/Cntr=0.3,0.1

Type RM Length L Ch R = 1 ,31188.91,988.044900,988.044900,988.044900
XS GIS Cut Line= 6
463221.404537127729209.965044826463283.425773899726477.289473937
463434.157088529724050.777325062463989.270977486719225.825636507
464212.193929381 716577.87691846464284.680154767712551.945792733
#Sta/Elev= 30
 1645.91 60.26591800.87558.101251990.88673.119572320.90449.662742810.97543.02278
2840.98134.155472870.98842.33808 4872.3217.709979965.76610.635799996.1084.569577
10076.9811.0827311468.0810.7262311498.255.39014111518.3711.1015415130.0213.26153
16570.7838.2286417040.8158.7881717130.8172.0777817160.8183.9234317220.8184.60696
17250.81102.460917360.81 147.76717540.82238.306617580.82253.586517630.82259.8041
17690.83253.1651 17920.9192.218818090.95 161.64618140.96155.939118354.08158.7608
#Mann= 3 , 0 , 0
 1645.91  0.0417       0 1645.91  0.0417       018354.08  0.0417       0
#XS Ineff= 2 , 0
       0                               0
Bank Sta=1645.91,18354.08
Exp/Cntr=0.3,0.1

Type RM Length L Ch R = 1 ,30200.87,988.044900,988.044900,988.044900
XS GIS Cut Line= 6
464972.671747944729205.189821928 464887.13915971722381.581728856
464693.563192827720215.422640063464659.759623432719481.135399832
464741.566476953715103.707439001464687.185524836712505.722405851
#Sta/Elev= 30
1643.59784.361231953.94599.672942274.05753.566142434.10646.063682684.18262.13388
2944.233107.19033014.245107.94663184.27469.966073324.298 59.83863444.31363.07948
3654.33135.327523854.34925.37106 4034.3631.148334604.37721.2261510010.275.114373
10070.7719.4462210151.449.46464511635.195.90004515256.16 13.312716016.1923.46929
16656.2152.7364417086.2683.91212 17206.3111.871517446.38205.584117516.41220.8777
17786.57228.669517896.68241.648618056.83 210.31218307.07 193.302 18356.4199.0563
#Mann= 3 , 0 , 0
1643.597  0.0522       01643.597  0.0522       0 18356.4  0.0522       0
#XS Ineff= 2 , 0
       0                               0
Bank Sta=1643.597,18356.4
Exp/Cntr=0.3,0.1

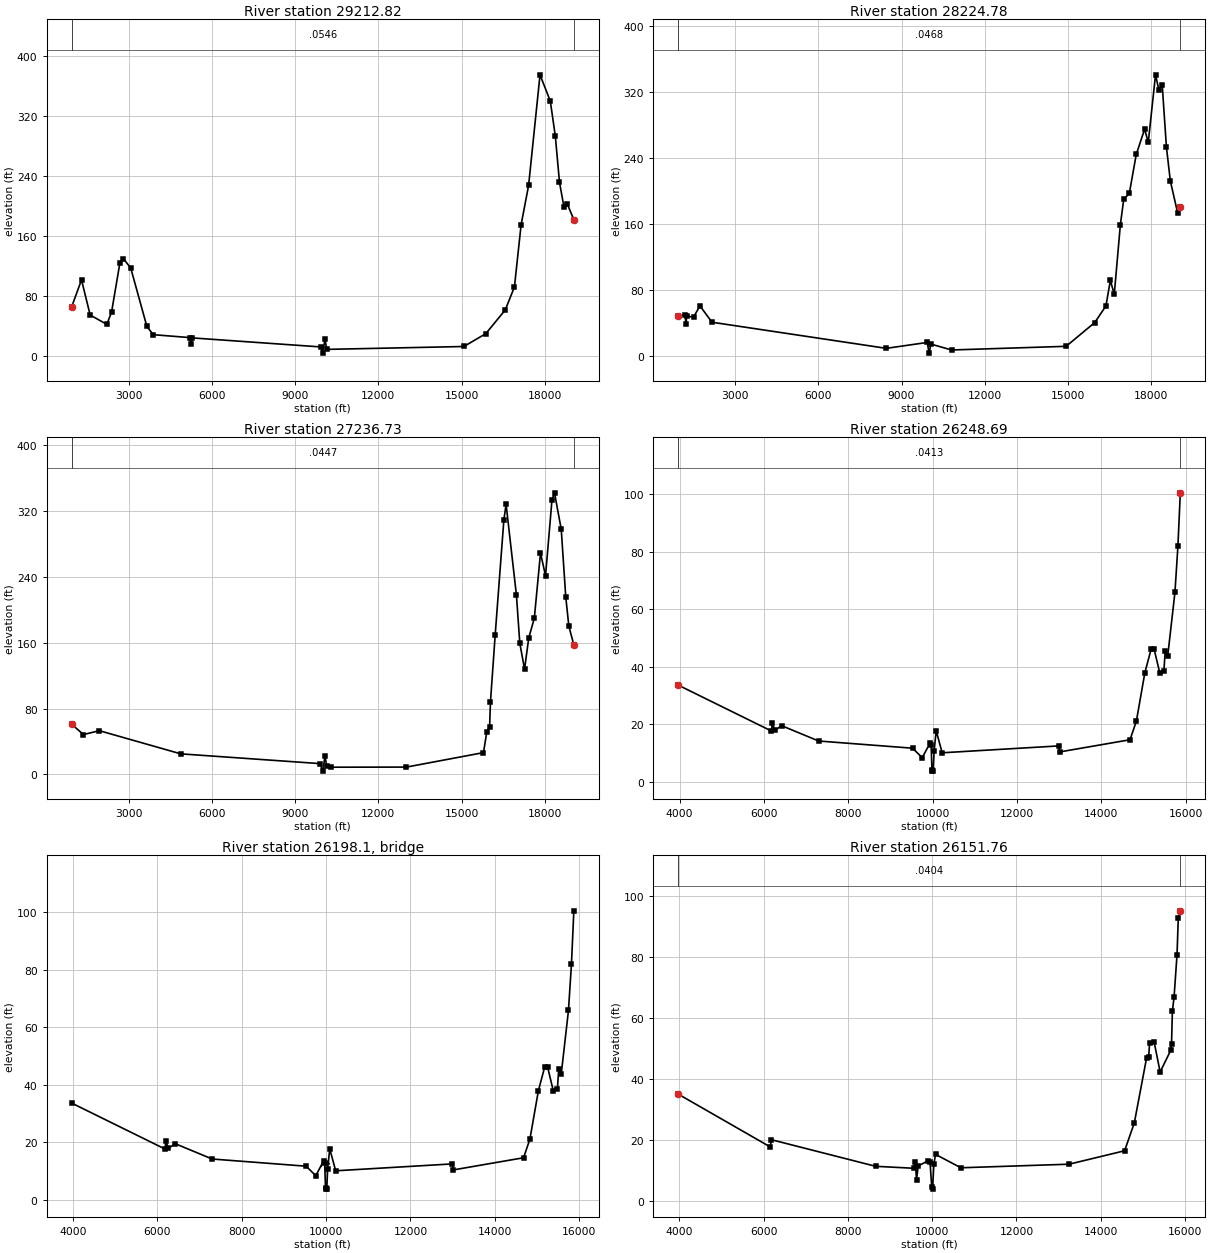
Type RM Length L Ch R = 1 ,29212.82,988.044900,988.044900,988.044900
XS GIS Cut Line= 6
466350.656264725729735.562109252465989.309992581722963.721654651
465599.738965923719583.220736402465524.464693145718707.787806458
465354.335919688713763.239098783465201.870769019711690.196350144
#Sta/Elev= 30
954.802465.899241306.107101.42211616.65154.63714 2217.6642.152152387.91158.35795
2688.355123.82592818.528129.39333078.845117.1674 3659.5539.57471 3889.8328.43423
5221.24524.527355261.28816.34365 5301.3324.129959928.38812.122049998.9983.880959
 10079.722.6276110140.228.87150115083.3312.7028415873.6629.82445 16574.261.37093
16904.5391.9543817144.88174.740517415.33 227.14317826.17374.285818197.15339.2982
18377.64292.738518528.19231.177818688.87198.541118809.39202.378919045.19181.5442
#Mann= 3 , 0 , 0
954.8024  0.0546       0954.8024  0.0546       019045.19  0.0546       0
#XS Ineff= 2 , 0
       0                               0
Bank Sta=954.8024,19045.19
Exp/Cntr=0.3,0.1

Type RM Length L Ch R = 1 ,28224.78,988.044900,988.044900,988.044900
XS GIS Cut Line= 6
 467572.11282251 729576.07045554467079.255077622723547.969923787
466915.445830452722020.083494201 466440.71826703718368.288613105
466076.671373906713636.456047631465855.327977401711567.467019572
#Sta/Elev= 30
952.690548.689841194.71850.436161234.87739.517751254.95648.515451505.87947.81817
1736.70461.166142168.21641.416838452.1479.8061689925.04616.936769995.7184.016175
 10056.314.9873310803.457.81630914932.1112.2629915964.6541.0698616365.7961.07475
16526.3392.02202 16666.875.1453716887.55159.671617007.99190.095517208.85197.2997
17459.92244.509217761.34275.081317892.07258.948318153.54340.795718274.22322.6382
 18394.9328.592618545.97253.593118687.04 212.56618949.03174.006919047.31180.2874
#Mann= 3 , 0 , 0
952.6905  0.0468       0952.6905  0.0468       019047.31  0.0468       0
#XS Ineff= 2 , 0
       0                15394.07       0
Bank Sta=952.6905,19047.31
Exp/Cntr=0.3,0.1

Type RM Length L Ch R = 1 ,27236.73,988.044900,988.044900,988.044900
XS GIS Cut Line= 6
468729.264404275729424.050679923468034.480085561722948.795317812
467868.669411844721648.876474894467422.831354473718434.323805401
466862.424379788713518.499979116466568.728650733711456.133499162
#Sta/Elev= 30
950.338560.882631371.91848.512871945.35953.183624881.17925.032289897.89813.17366
9998.8854.03569310079.6822.6434810140.289.72420910301.878.80094413015.298.947036
15791.88 26.546415912.6551.9148716013.2958.1414316043.4988.1100116214.58169.9039
16526.72309.3503 16607.3328.339916979.98217.925317100.98159.6887 17272.4127.9481
17423.65165.940317625.32190.063617847.46269.161518029.26241.446418261.56333.8778
18352.46342.345118595.25298.014218757.23216.187418868.59180.396219049.66157.3877
#Mann= 3 , 0 , 0
950.3385  0.0447       0950.3385  0.0447       019049.66  0.0447       0
#XS Ineff= 2 , 0
       0                 14584.7       0
Bank Sta=950.3385,19049.66
Exp/Cntr=0.3,0.1

Type RM Length L Ch R = 1 ,26248.69,96.928400,96.928400,96.928400
XS GIS Cut Line= 6
469129.703544438726289.170136377 468645.31844902 722322.33473821
468639.691827714721769.050304219468694.082500935720529.318064049
468472.455111086 718071.19872871 468191.49868539714437.916621342
#Sta/Elev= 30
 3969.1533.652246179.61817.679216199.76620.358426260.212 17.9101  6421.4 19.5375
7297.86214.205279524.46411.704259754.4698.4033759944.94113.667469964.99212.97371
9985.0443.9979329995.0693.72363210015.183.80516410035.29 10.729910085.5817.75194
10226.3710.1062412986.4912.4950813016.5910.41417   1468114.6443214831.5821.14202
15032.4237.9711315183.0646.2996115253.3646.0722715383.9138.0468515484.3438.70948
15514.4645.4945915574.72  43.83115745.4465.8946415815.7481.9083115873.06100.5787
#Mann= 3 , 0 , 0
 3969.15  0.0413       0 3969.15  0.0413       015873.06  0.0413       0
#XS Ineff= 2 , 0
       0                13504.64       0
Bank Sta=3969.15,15873.06
Exp/Cntr=0.3,0.1

Type RM Length L Ch R = 3 , 26198.1,,,
BEGIN DESCRIPTION:
END DESCRIPTION:
Bridge Culvert--1,0,-1,-1, 0
Deck Dist Width WeirC Skew NumUp NumDn MinLoCord MaxHiCord MaxSubmerge Is_Ogee
40.964200,15.000000,2.6,0, 21, 21, , , 0.95, 0, 0,0,,
 9884.09 9887.67 9897.70 9907.73 9916.23 9917.76 9927.76 9937.77 9947.77 9957.77
 9958.72 9966.99 9966.9910036.9910036.9910041.6010047.8510049.6810057.8610067.88
10074.56
   11.70   11.79   12.12   12.42   12.62   12.66   12.93   13.18   13.65   13.82
   13.54   13.49   13.49   13.06   13.06   13.03   13.20   13.13   12.84   12.71
   12.50
 -988.30 -988.21 -987.88 -987.58 -987.38 -987.34 -987.07 -986.82 -986.35 -986.18
 -986.46 -986.51    9.49    9.06 -986.94 -986.97 -986.80 -986.87 -987.16 -987.29
 -987.50
 9884.09 9887.67 9897.70 9907.73 9916.23 9917.76 9927.76 9937.77 9947.77 9957.77
 9958.72 9963.45 9963.4510033.4510033.4510041.6010047.8510049.6810057.8610067.88
10074.56
   11.70   11.79   12.12   12.42   12.62   12.66   12.93   13.18   13.65   13.82
   13.54   13.51   13.51   13.08   13.08   13.03   13.20   13.13   12.84   12.71
   12.50
 -988.30 -988.21 -987.88 -987.58 -987.38 -987.34 -987.07 -986.82 -986.35 -986.18
 -986.46 -986.49    9.51    9.08 -986.92 -986.97 -986.80 -986.87 -987.16 -987.29
 -987.50
BR Coef=-1 , 0 , 0 ,, 0 ,,,0.8,0,1,0,
WSPro=,,,, 1 ,,,, 0 ,,,, 0 ,,,,-1 ,-1 ,-1 , 0 , 0 , 0 , 0 , 0
BC Design=,, 0 ,, 0 ,,,,,,

Type RM Length L Ch R = 1 ,26151.76,923.921700,923.921700,923.921700
XS GIS Cut Line= 6
469248.259878606726262.841396034468707.211284012722110.398666888
468774.849896342720290.198504657468573.576858371 717349.10399875
468446.818611801716265.249778867  468295.6232346714407.372708127
#Sta/Elev= 30
3976.06335.064136163.066 17.73266183.24320.137458659.67711.41231 9560.6310.77003
9600.66312.961269630.6877.045903 9670.7211.52193 9890.8813.131999950.91812.71751
9990.9954.74567810011.133.93296810041.2512.0801610081.3915.31735 10683.410.92951
13250.8412.1032414567.9416.5030514798.9325.6978915089.6946.9715215139.8247.30884
15159.8851.7563215270.1752.0519115410.5342.3069815661.1949.3964215681.2451.54241
 15701.362.27308 15741.466.8787915811.5980.8124315841.6792.8335815889.4295.13406
#Mann= 3 , 0 , 0
3976.063  0.0404       03976.063  0.0404       015889.42  0.0404       0
#XS Ineff= 2 , 0
       0                13396.57       0
Bank Sta=3976.063,15889.42
Exp/Cntr=0.3,0.1

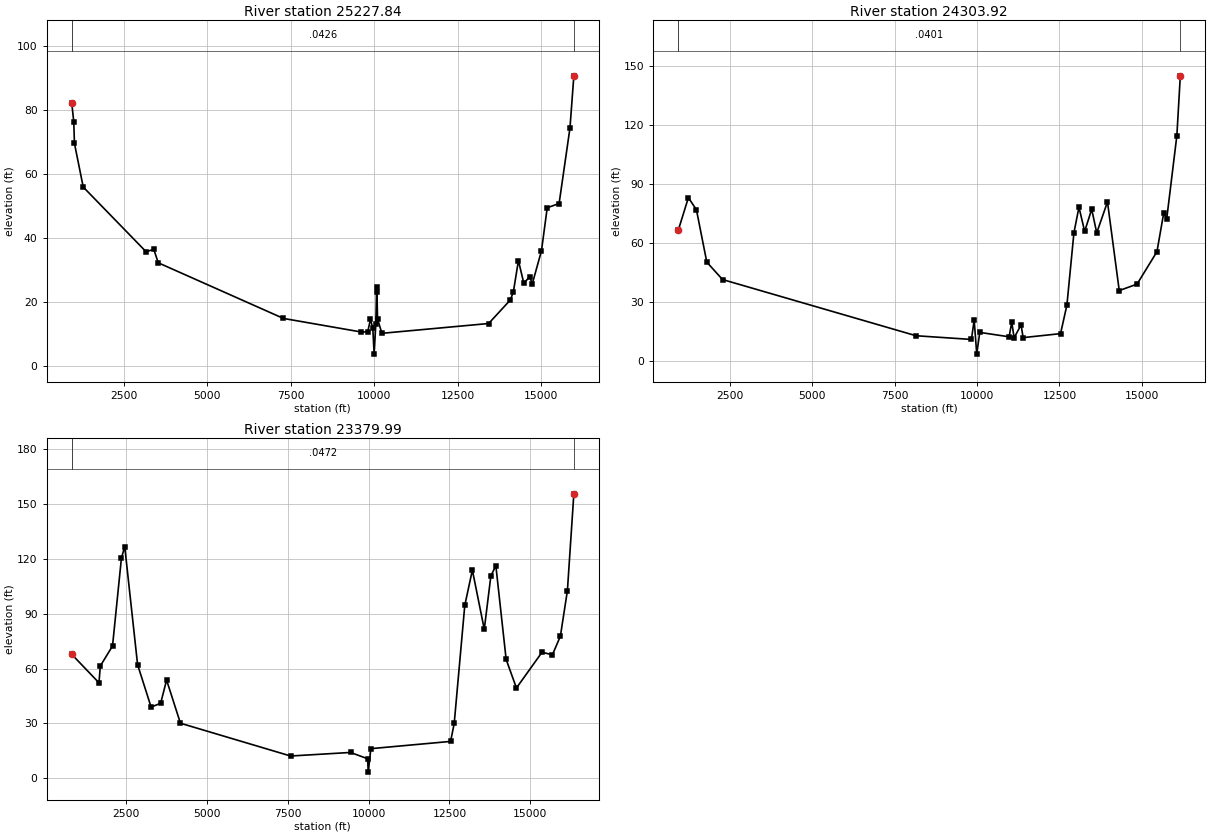
Type RM Length L Ch R = 1 ,25227.84,923.921600,923.921600,923.921600
XS GIS Cut Line= 6
470996.269260287729103.963657439470479.802694678725694.425963402
469556.082354605719212.041741744469397.652184308718147.382255331
469096.472763211716257.089919865468741.073550224714241.024428278
#Sta/Elev= 30
945.898782.247621005.57176.390391025.81169.669151288.93456.001753170.47435.78392
3403.00136.508753534.42932.316637283.48414.913289616.46810.662699808.27810.73325
 9889.0414.584289959.70711.9206810000.093.74863810050.5513.2988710070.7423.17355
10080.8324.6794410101.0214.7781410232.2310.2565513428.2113.32275 14076.920.66669
14168.1923.1505914320.3433.0272814482.6425.8601314655.0927.9872214736.2425.76533
15010.3736.0657515182.9949.5308815538.6550.8554615863.9974.4893715979.9590.78486
#Mann= 3 , 0 , 0
945.8987  0.0426       0945.8987  0.0426       015979.95  0.0426       0
#XS Ineff= 2 , 0
       0                12855.62       0
Bank Sta=945.8987,15979.95
Exp/Cntr=0.3,0.1

Type RM Length L Ch R = 1 ,24303.92,923.921700,923.921700,923.921700
XS GIS Cut Line= 6
472045.420753926728957.898539871471638.364487559726619.825769871
 471194.13330096723934.449962214470265.610223234717823.483425453
469889.341186881 715751.88676846469512.763037205713952.845894679
#Sta/Elev= 30
944.0582  66.3831251.64183.009981495.353 76.88031810.14750.211952287.23341.36883
8153.64712.783349831.29610.902059915.14520.667129993.0573.43300310084.0414.48711
10973.6812.2492511054.5919.67673 11125.411.74498 11337.8 18.2941 11398.511.82767
12533.2713.8524112726.0428.3672612939.3265.1690813091.6678.1590613264.3365.84795
13477.9477.1088913630.5365.1002313956.0780.8415514312.5835.7605814853.1339.04092
15455.7755.5265715660.2475.1501515752.2472.3143916059.42114.574916164.02144.9773
#Mann= 3 , 0 , 0
944.0582  0.0401       0944.0582  0.0401       016164.02  0.0401       0
#XS Ineff= 2 , 0
       0                               0
Bank Sta=944.0582,16164.02
Exp/Cntr=0.3,0.1

Type RM Length L Ch R = 1 ,23379.99,923.921700,923.921700,923.921700
XS GIS Cut Line= 6
473125.442087352728909.747461274472032.240909338723141.138609722
471346.840288341718759.325132966 471123.79572472717476.184943646
470739.607703358715632.253100172470264.106942808713672.265183669
#Sta/Elev= 30
833.211167.776021674.12152.227831714.88261.429142091.92772.345542367.068120.4047
2468.972 126.7222866.33862.138483283.86438.969193579.07741.046533762.28153.73106
4189.75730.139977593.46412.219159445.58714.164689971.15310.725299991.3673.411085
10072.2416.2406812535.2120.1994512647.2730.0293212973.3194.5156313208.16113.8375
13575.7581.4893313780.36110.721413933.82116.226914251.4165.0096814569.3749.39713
15360.6668.9548915679.8467.50907 15927.377.7275416143.97 102.61216342.85155.5196
#Mann= 3 , 0 , 0
833.2111  0.0472       0833.2111  0.0472       016342.85  0.0472       0
#XS Ineff= 2 , 0
       0                               0
Bank Sta=833.2111,16342.85
Exp/Cntr=0.3,0.1