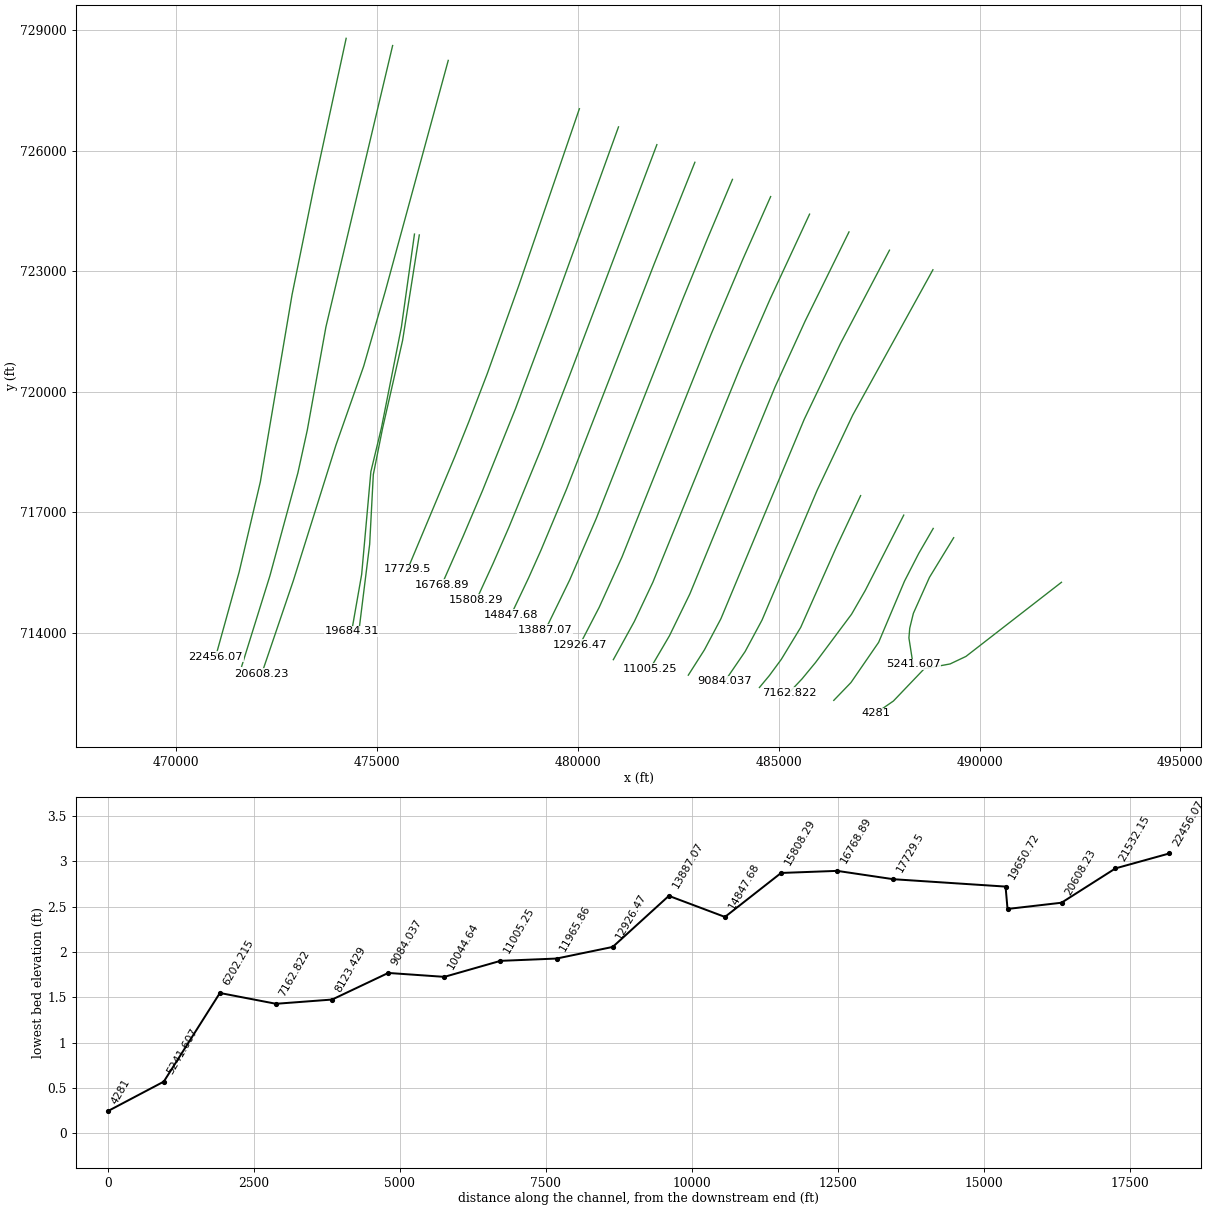
HEC-RAS study 691_ras.prj: 691

--- 691_ras.g01 (geometry) --- (continued)

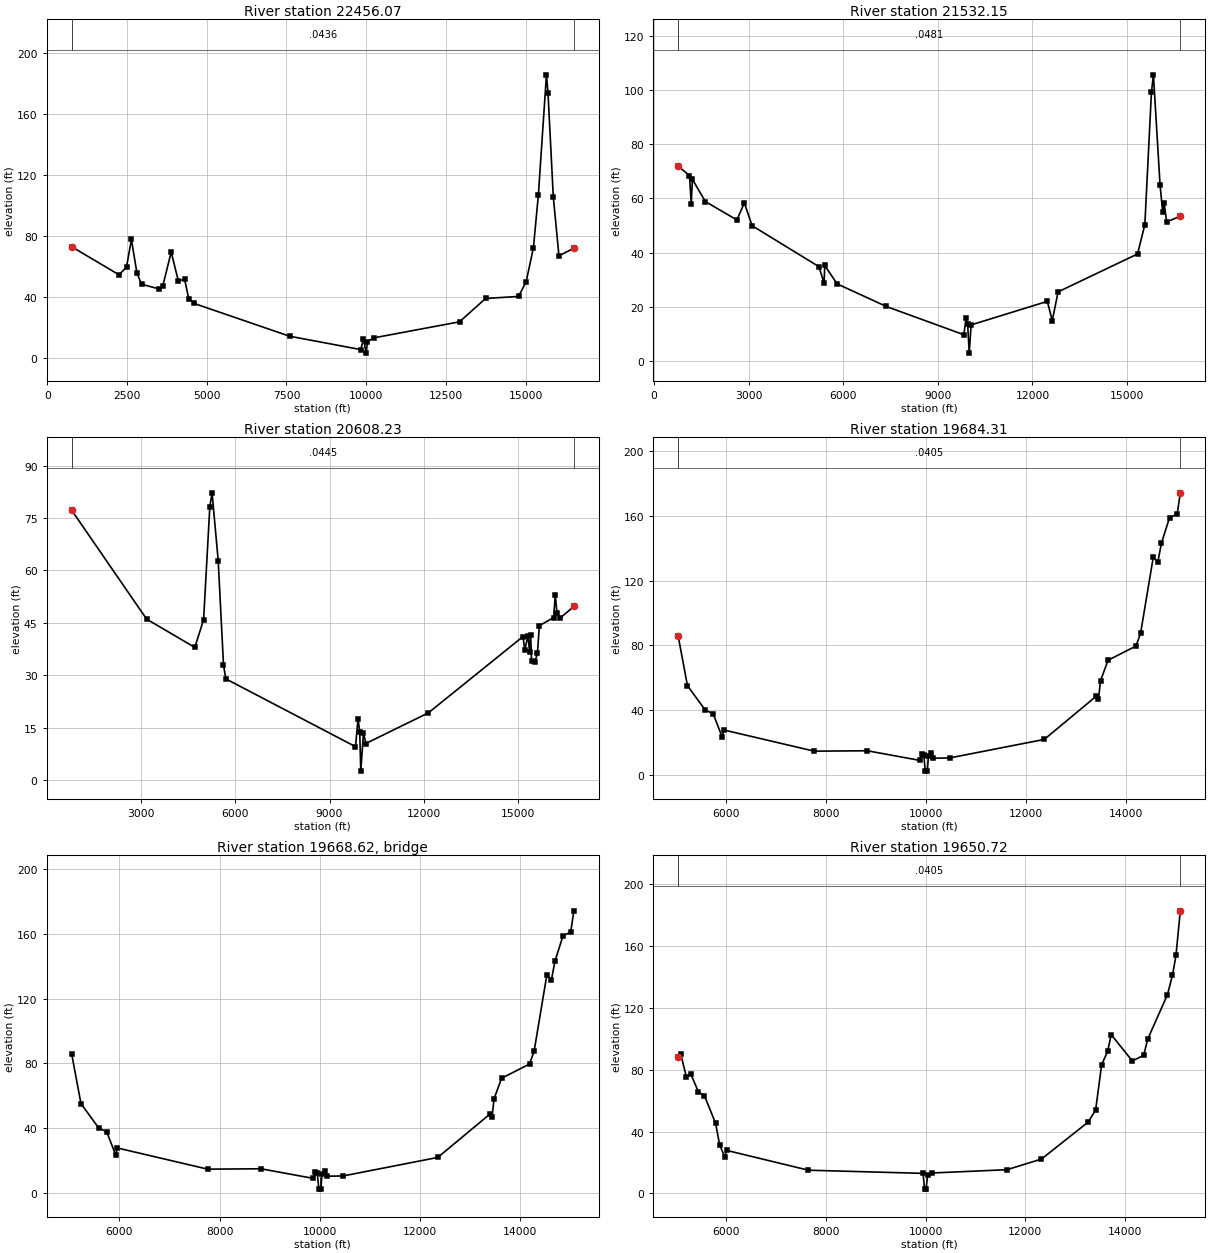
Type RM Length L Ch R = 1 ,22456.07,923.921700,923.921700,923.921700
XS GIS Cut Line= 6
474226.372750521728801.459199324 473429.98347649725127.038226485
472878.942066133  722417.4019932472089.562803745717758.426037565
471561.402914643715512.599231094470976.655833385713406.172023323
#Sta/Elev= 30
767.689972.963792248.93754.558062484.24159.599532637.69777.754592811.61455.65331
 2954.8448.368223497.04645.317333619.71747.017663885.50569.501934110.40350.46804
4304.63351.702474437.52738.618044600.78935.753757600.376 14.19129830.9055.413092
9911.77412.3870710002.753.08928710036.3310.6990510245.34 13.141812926.7423.66119
13745.7839.0099114778.4140.3355315016.6750.0455415244.5972.3800215400.31107.2064
15652.79185.951315701.35174.134115867.71105.8181 16044.667.0425216512.1272.01974
#Mann= 3 , 0 , 0
767.6899  0.0436       0767.6899  0.0436       016512.12  0.0436       0
#XS Ineff= 2 , 0
       0                12443.82       0
Bank Sta=767.6899,16512.12
Exp/Cntr=0.3,0.1

Type RM Length L Ch R = 1 ,21532.15,923.921600,923.921600,923.921600
XS GIS Cut Line= 6
 475383.40412423728621.578099564473722.140784502721614.428643584
473257.616906315 719041.89439781473024.960496753717984.298606053
472328.189090163715419.997674137471624.643219944 713164.18861161
#Sta/Elev= 30
768.543471.862211125.464  68.4291180.39158.047751218.141 67.03151630.00558.83417
2628.10252.049752864.76458.351493111.58849.92423 5229.03 34.83615393.44728.76425
5413.99935.267635804.27428.481217364.62420.146049824.164 9.713189894.82815.73184
9945.18613.733929995.544 2.9239210055.99 13.335512472.7322.0215112627.8414.91443
12814.2625.5300215333.7839.5112615564.1850.3131615773.6899.1979915836.67105.5933
16046.6664.9258316130.65 54.953316172.6558.4507816256.6451.3547116689.0153.43033
#Mann= 3 , 0 , 0
768.5434  0.0481       0768.5434  0.0481       016689.01  0.0481       0
#XS Ineff= 2 , 0
       0                12551.71       0
Bank Sta=768.5434,16689.01
Exp/Cntr=0.3,0.1

Type RM Length L Ch R = 1 ,20608.23,923.921700,923.921700,923.921700
XS GIS Cut Line= 6
476768.330824703728251.690844163475199.358934641722498.207066476
474662.877306014720638.244266957473973.209102452718677.069374084
472909.662020266715293.244957402 472122.64524356712978.215502851
#Sta/Elev= 30
799.849577.171553180.74846.054944714.10637.95187 4993.8445.91819 5190.6978.15977
5263.21482.197015457.74862.791155626.06633.061875698.65628.958849825.3029.550264
9906.85717.56405 9960.63 13.75769992.8932.54445310079.02 13.494410154.3810.45151
12143.9719.2205715155.6241.07331 15208.3 37.265815313.8141.2998215362.1336.62735
15398.2741.4947915424.5334.1966915535.5133.8279815611.7236.2454415674.1244.16559
16127.6446.5012716180.5652.9927316233.4847.8268116328.7346.3071516771.1949.66566
#Mann= 3 , 0 , 0
799.8495  0.0445       0799.8495  0.0445       016771.19  0.0445       0
#XS Ineff= 2 , 0
       0                               0
Bank Sta=799.8495,16771.19
Exp/Cntr=0.3,0.1

Type RM Length L Ch R = 1 ,19684.31,33.591200,33.591200,33.591200
XS GIS Cut Line= 6
475927.310322911723927.407185525475602.421561509721616.909279838
475103.356355578719097.035405964474841.544839144718011.992403209
474611.962277859715451.563160107474363.136968642714032.756186247
#Sta/Elev= 30
5047.13885.57232  5231.155.212025584.084 40.24485745.44837.811115926.98223.37193
5957.23827.864947763.65514.793128825.51215.037699872.4959.1098949912.77112.75066
9953.09112.219739983.9472.66980110025.092.47568710045.6811.50082 10097.313.94316
10138.5910.4511410468.9410.5987512361.37 22.035613404.4148.8121513444.6446.81483
13484.8858.1967813635.7770.8725414194.1379.64463 14285.587.4891314539.32134.4425
14630.69 131.49914701.76143.0411 14864.2158.854515016.49160.991915079.68174.1548
#Mann= 3 , 0 , 0
5047.138  0.0405       05047.138  0.0405       015079.68  0.0405       0
#XS Ineff= 2 , 0
       06599.246                       0
Bank Sta=5047.138,15079.68
Exp/Cntr=0.3,0.1

Type RM Length L Ch R = 3 ,19668.62,,,
BEGIN DESCRIPTION:
END DESCRIPTION:
Bridge Culvert--1,0,-1,-1, 0
Deck Dist Width WeirC Skew NumUp NumDn MinLoCord MaxHiCord MaxSubmerge Is_Ogee
9.295600,15.000000,2.6,0, 10, 10, , , 0.95, 0, 0,0,,
 9948.66 9955.09 9956.13 9956.1310041.1610043.2410043.2410049.6710052.3910054.15
   12.34   12.49   12.48   12.48   12.07   12.03   12.03   11.92   11.82   11.75
 -987.66 -987.51 -987.52    9.98    9.57    9.53 -987.97 -988.08 -988.18 -988.25
 9948.66 9953.79 9953.79 9955.0910038.8410038.8410041.1610049.6710052.3910054.15
   12.34   12.46   12.46   12.49   12.08   12.08   12.07   11.92   11.82   11.75
 -987.66 -987.54    9.96    9.99    9.58 -987.92 -987.93 -988.08 -988.18 -988.25
Pier Skew, UpSta & Num, DnSta & Num=  ,9999.68, 2 ,9996.32, 2 , 0 , 0 , 0 ,,
    3.00    3.00
 -987.73   12.27
    3.00    3.00
 -987.71   12.29
BR Coef=-1 , 0 , 0 ,, 0 ,,,0.8,0,1,0,
WSPro=,,,, 1 ,,,, 0 ,,,, 0 ,,,,-1 ,-1 ,-1 , 0 , 0 , 0 , 0 , 0
BC Design=,, 0 ,, 0 ,,,,,,

Type RM Length L Ch R = 1 ,19650.72,1921.214600,1921.214600,1921.214600
XS GIS Cut Line= 6
476047.155573189723905.265427545475631.112731069721276.713981986
 475132.63902244719088.018124476 474902.50744018717939.356112659
474811.712076962716203.867598325474534.288194805713969.402807429
#Sta/Elev= 30
5041.16788.007725092.01889.98616  5203.375.542555294.34977.176385446.09765.62599
5567.495 63.09735790.05945.339145870.99131.460385972.15623.580946012.62227.78221
7653.52214.960039950.882 12.92939981.4072.81168210011.932.72281610042.4411.77196
10133.8213.1693911635.2615.2982212325.6922.1859913260.44 46.0693 13411.6 53.8766
13532.5283.2939713653.4491.8411113723.98102.7332 14147.285.6696414373.9489.27656
14459.58100.013514852.58128.593914953.34141.1578 15023.2153.959215110.14182.8149
#Mann= 3 , 0 , 0
5041.167  0.0405       05041.167  0.0405       015110.14  0.0405       0
#XS Ineff= 2 , 0
       06582.283                       0
Bank Sta=5041.167,15110.14
Exp/Cntr=0.3,0.1

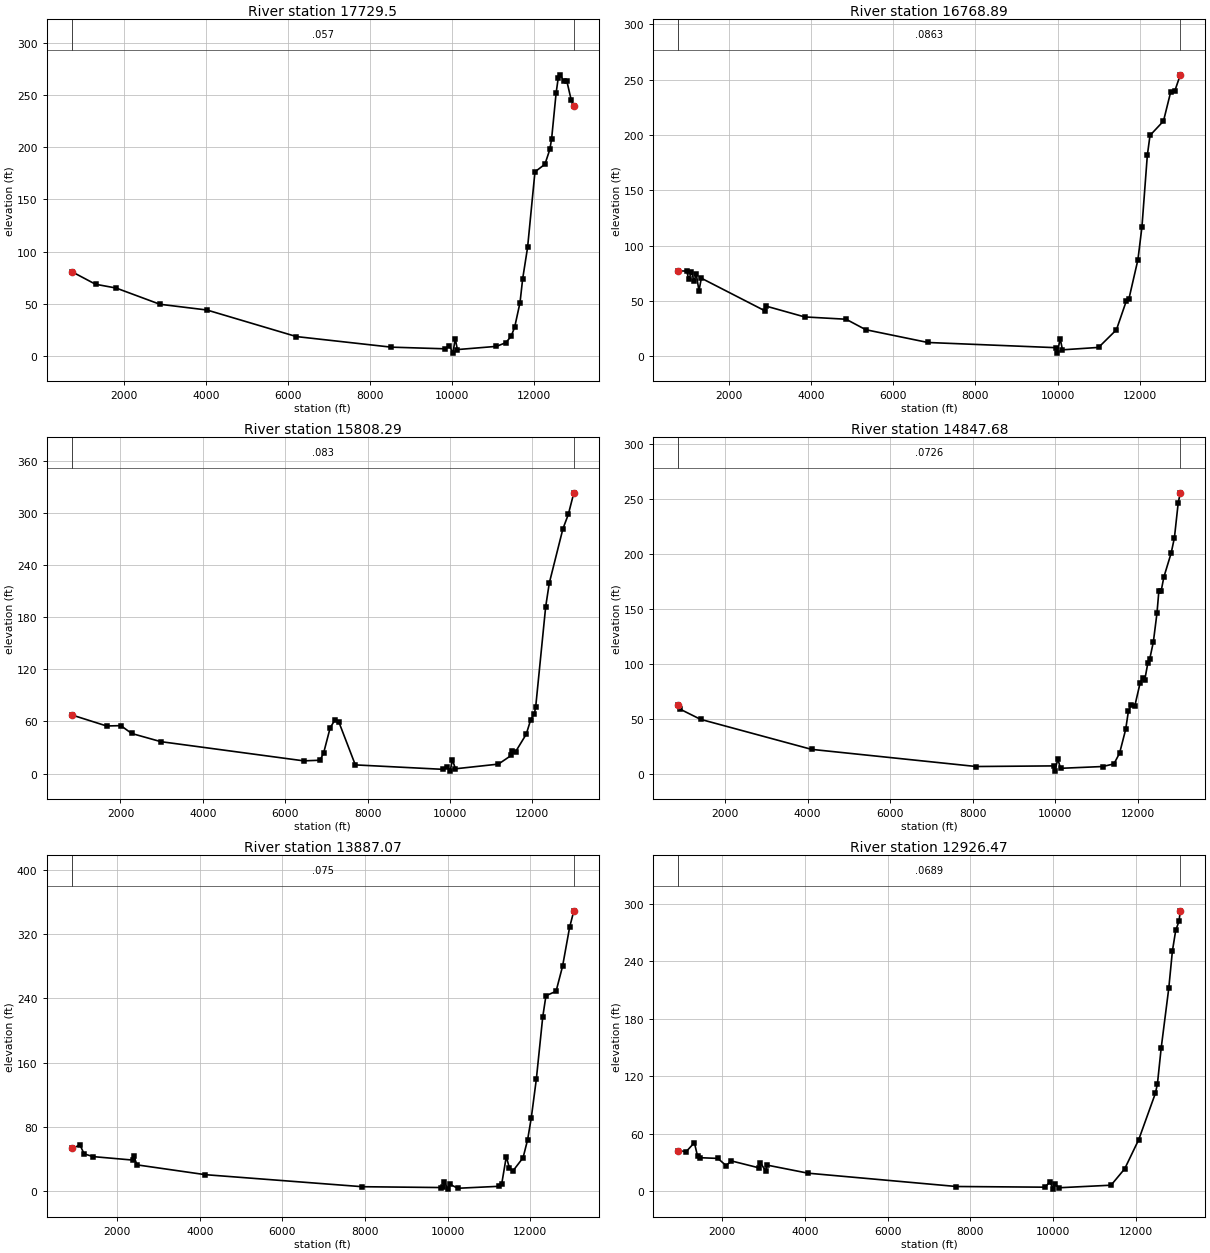
Type RM Length L Ch R = 1 , 17729.5,960.607300,960.607300,960.607300
XS GIS Cut Line= 6
480033.988721822727047.900077249478528.433443084722656.246662991
477742.711281263720459.168648739477280.987714324719255.387380138
 476928.69494531 718376.82241612475754.400646068715575.980169647
#Sta/Elev= 30
715.368980.791711295.54368.734561797.126 65.12142864.68749.582784013.65844.08067
6196.245  18.646  8508.78.5245219810.5346.9520959929.1749.74125910015.612.804301
10069.6716.7480910123.736.215024 11076.4 9.2786611303.9812.7914211434.1118.86741
11520.95 27.7375 11651.251.2378211716.3374.1501311835.73104.009712015.57176.3509
12259.05  183.6412378.45  197.8412421.87207.931812530.54251.419212584.89266.6104
12631.17269.233912726.21262.904212791.43263.529112900.13 245.14312964.29239.4907
#Mann= 3 , 0 , 0
715.3689   0.057       0715.3689   0.057       012964.29   0.057       0
#XS Ineff= 2 , 0
       0 5848.81                       0
Bank Sta=715.3689,12964.29
Exp/Cntr=0.3,0.1

Type RM Length L Ch R = 1 ,16768.89,960.607300,960.607300,960.607300
XS GIS Cut Line= 6
481007.989238502  726596.4320266479317.599878302721921.309712058
 478444.75612287719584.722400221477621.089264024717538.356148083
477141.353724961716407.556884559476609.675926369715201.196619854
#Sta/Elev= 30
768.435777.07107 972.36977.072991025.57669.603211089.42576.321091153.27467.95064
1206.48274.477811272.66659.207481331.15470.555062876.471 41.12932897.72745.43856
  3843.635.606254853.23933.503775331.73924.049746843.80312.504929967.3477.805858
9988.9752.89635410064.8115.8372510118.895.87956910997.498.05558611431.9523.96941
11671.2449.8583811736.6751.9837911954.7887.2103112052.92116.881912183.79181.4344
12249.29199.531112577.27212.497612752.38238.758912851.86239.593412986.79254.2486
#Mann= 3 , 0 , 0
768.4357  0.0863       0768.4357  0.0863       012986.79  0.0863       0
#XS Ineff= 2 , 0
       0                               0
Bank Sta=768.4357,12986.79
Exp/Cntr=0.3,0.1

Type RM Length L Ch R = 1 ,15808.29,960.607300,960.607300,960.607300
XS GIS Cut Line= 6
481963.084333129  726153.7270042479780.560779789720382.300258348
479097.033303722718617.205376645478277.559519287716623.629425208
477884.016686057715723.661647393477471.184966341714823.681422565
#Sta/Elev= 30
817.679667.520861663.11954.83189 2009.4655.200492273.30746.180892979.02236.79645
6450.68914.691256846.18615.410756931.69823.563797092.24252.779517210.056 61.9118
7306.449  58.9337702.73210.048499821.1894.9542369939.9558.04807510004.742.873336
10061.2515.7078310134.55 5.57032 11176.510.9443111492.4521.0702611514.24 26.0745
11595.6225.3215711853.1645.3702411962.4962.2000412050.07 68.917112082.9977.05133
 12324.4191.866812412.19219.182312742.65281.576112874.88298.317613008.78323.0871
#Mann= 3 , 0 , 0
817.6796   0.083       0817.6796   0.083       013008.78   0.083       0
#XS Ineff= 2 , 0
       0                               0
Bank Sta=817.6796,13008.78
Exp/Cntr=0.3,0.1

Type RM Length L Ch R = 1 ,14847.68,960.607300,960.607300,960.607300
XS GIS Cut Line= 6
482909.478685833725715.054943721481901.053521539723196.738749613
479716.811838044717583.248597197479078.292175693716058.106451026
478766.189342827715359.857064127478332.366128985714446.309901859
#Sta/Elev= 30
864.051762.78727896.536759.076521403.97949.587214093.86122.21834 8081.856.596846
 9965.477.1542869987.0612.38751910062.7113.3019210127.664.95238111148.236.581298
11421.188.96291911558.6818.7868111705.6140.3167711771.4756.8446811837.3362.68502
11925.1561.4825112057.0582.8777712123.2187.6396612167.3285.28863 12244.5101.2048
12288.61104.454712376.82120.097612465.18146.519512509.55166.237212565.02166.3995
12631.59179.2162 12809.1201.1879 12887.2215.062412978.97246.788113029.97255.9435
#Mann= 3 , 0 , 0
864.0517  0.0726       0864.0517  0.0726       013029.97  0.0726       0
#XS Ineff= 2 , 0
       04676.557                       0
Bank Sta=864.0517,13029.97
Exp/Cntr=0.3,0.1

Type RM Length L Ch R = 1 ,13887.07,960.607300,960.607300,960.607300
XS GIS Cut Line= 6
483845.440558321725289.310237413483219.651650852 723804.61204902
482603.012819397722294.498583884480454.470364773716847.234865801
479793.318260088715316.561492442479187.253747624714071.696226277
#Sta/Elev= 30
902.888353.428771103.39357.452941201.28146.531871418.40343.114082372.80738.82473
2405.31443.741342481.16332.829884133.92220.623187937.1735.6221779830.4434.600014
9895.3085.3014359920.656 11.927810003.422.62033410057.598.65584810241.783.696831
11249.796.14812111308.329.29369611417.9742.9709411494.7228.8605711582.4425.51418
 11824.541.7387611934.7464.2636912022.9691.3445112144.97139.328212300.27216.9847
12377.92243.412512623.03249.018712779.72280.015912949.87328.423913053.16 349.164
#Mann= 3 , 0 , 0
902.8883   0.075       0902.8883   0.075       013053.16   0.075       0
#XS Ineff= 2 , 0
       04970.938                       0
Bank Sta=902.8883,13053.16
Exp/Cntr=0.3,0.1

Type RM Length L Ch R = 1 ,12926.47,960.607300,960.607300,960.607300
XS GIS Cut Line= 6
484796.214725541724860.529730628484109.018075444723311.209274843
483309.259321344721423.478212888481095.706610003715888.644311139
480528.431380219714636.556355681480041.743609413713697.256848642
#Sta/Elev= 30
937.579542.169371130.15641.204561327.638 50.54111404.26736.56624 1458.9834.86136
1895.79434.112432093.843 26.6533 2224.4531.476922900.62624.145612922.40829.72164
  3053.120.905663085.77327.121124074.08818.701667664.2564.7962969803.557 4.08993
9922.1959.39507610008.642.05624610051.917.26893510138.463.48713611401.896.155316
11732.3123.2996212071.7253.7844812473.97102.070512523.72 112.02112613.82149.2075
 12797.3211.548812885.46250.620112966.68 272.36713044.93281.531513076.64292.4945
#Mann= 3 , 0 , 0
937.5795  0.0689       0937.5795  0.0689       013076.64  0.0689       0
#XS Ineff= 2 , 0
       05263.732                       0
Bank Sta=937.5795,13076.64
Exp/Cntr=0.3,0.1

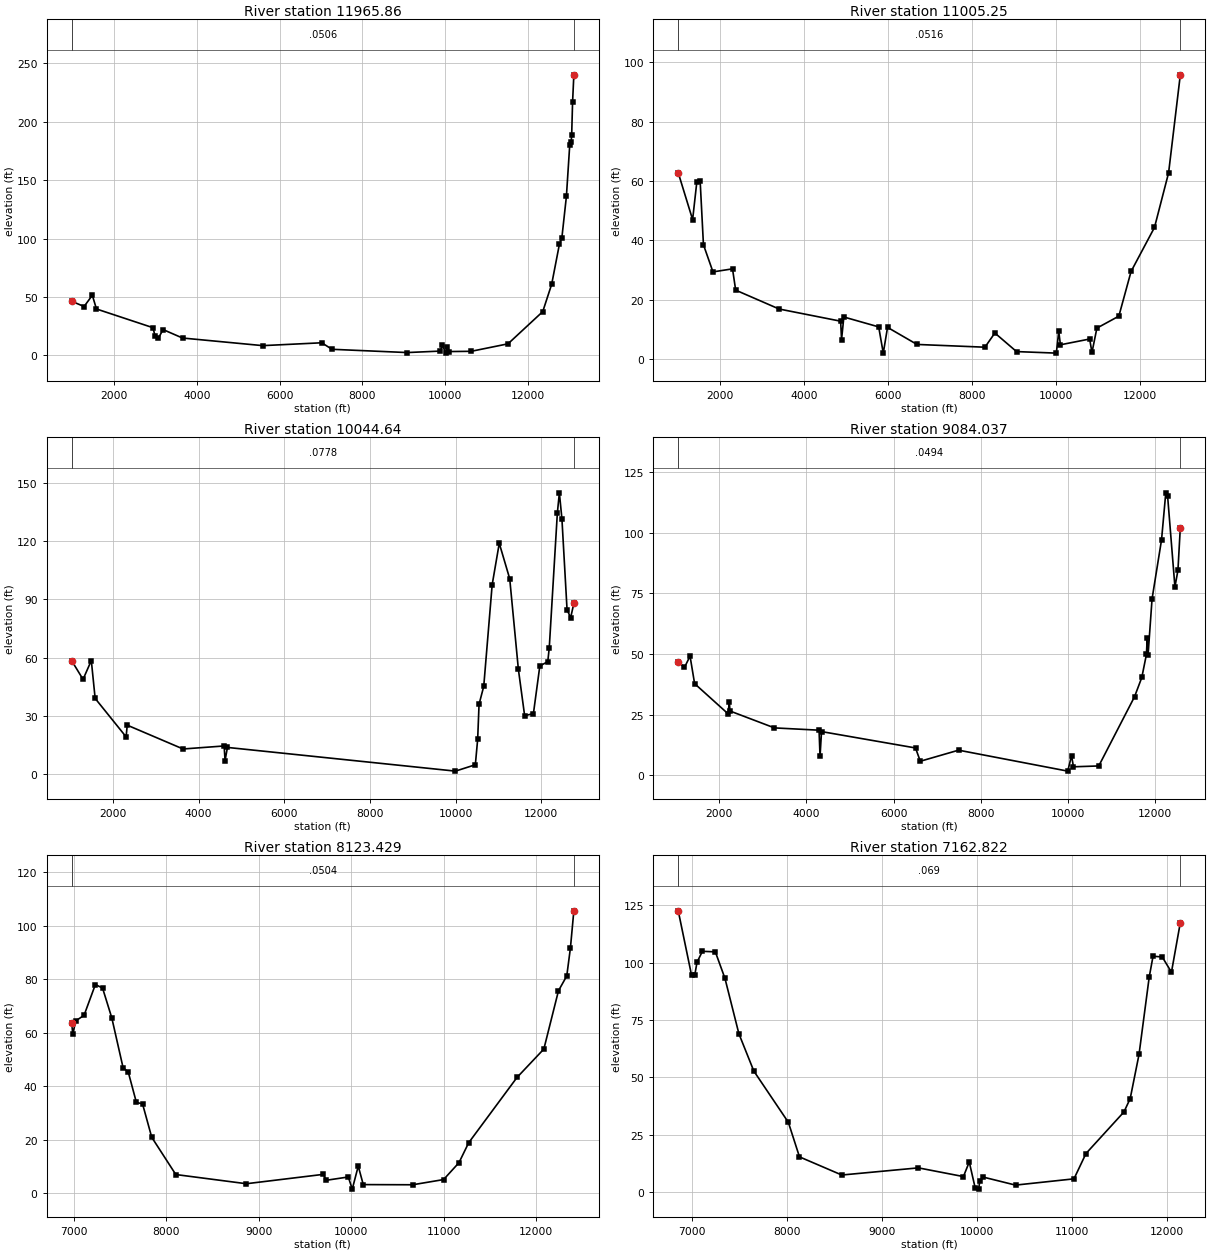
Type RM Length L Ch R = 1 ,11965.86,960.607300,960.607300,960.607300
XS GIS Cut Line= 6
485765.521965094724423.391171614484782.680147642722308.452728447
484039.646743384720605.789760544481862.998010228715256.632772474
 481403.30484822714283.475508576480879.266203923713330.252565657
#Sta/Elev= 30
976.853646.283771274.22641.831941473.66351.436441573.08539.716782940.00123.68027
 2988.4616.477933071.327 14.81143182.29722.093093652.25214.859535590.4458.343808
7016.61810.789047264.1795.2048439080.696 2.418539878.5443.6706829932.5788.765455
10008.471.92793110051.927.53490310095.363.27287210627.593.48970811515.919.891049
12355.0537.4591712571.0760.8809212756.7294.9099612817.29100.649612926.84136.1036
13007.99180.4507 13042.9182.868813054.54189.023613075.84216.685213106.61240.1307
#Mann= 3 , 0 , 0
976.8536  0.0506       0976.8536  0.0506       013106.61  0.0506       0
#XS Ineff= 2 , 0
       0  5563.7                       0
Bank Sta=976.8536,13106.61
Exp/Cntr=0.3,0.1

Type RM Length L Ch R = 1 ,11005.25,960.607300,960.607300,960.607300
XS GIS Cut Line= 6
486747.091195302723980.722695245485655.599698748721762.256440218
484907.979089145720125.394862006482784.753724017714967.092445006
482275.390919992713923.014984434481798.009444444713108.126315065
#Sta/Elev= 30
1005.94362.777291348.48846.960371449.31959.768971527.74360.057781606.167 38.5009
1832.96329.32041 2298.5330.34834 2373.8523.16475 3408.9516.789974873.59212.68258
4895.4886.4888974950.19914.098395780.05110.756515888.819 1.902515990.65410.59427
6692.2254.8341498310.0813.9035778546.601 8.691789062.6462.42178310010.721.904812
10067.989.25183310108.264.717725 10804.36.66420310858.962.11827110976.6710.34713
11499.4114.3850911790.5829.4725712348.0144.3226212684.1862.7594312963.2495.83554
#Mann= 3 , 0 , 0
1005.943  0.0516       01005.943  0.0516       012963.24  0.0516       0
#XS Ineff= 2 , 0
       05853.485                       0
Bank Sta=1005.943,12963.24
Exp/Cntr=0.3,0.1

Type RM Length L Ch R = 1 ,10044.64,960.607300,960.607300,960.607300
XS GIS Cut Line= 6
 487755.40038973723525.995019326 486534.67758081721202.041047021
485631.163832636 719311.63653948483557.338125025 714347.98012029
483145.804009241713571.831770693482745.760276038712943.895124029
#Sta/Elev= 30
1038.88858.434331302.273 48.92151495.31458.591461584.80839.121492308.03619.34383
 2333.8925.366793638.36413.113394596.53514.669864618.7047.1741254674.08113.91321
9998.2311.72559510462.884.99971910517.0918.0052810549.76 36.114510659.13 45.3197
   1085697.5951711021.67118.903811265.91100.665611467.7354.1390511614.4330.22272
11819.2531.3231511968.86 55.809912154.6958.0339212189.6465.2970712378.08 134.476
12425.29144.856312484.96131.456512604.8284.6947612688.76 80.644812763.3387.99675
#Mann= 3 , 0 , 0
1038.888  0.0778       01038.888  0.0778       012763.33  0.0778       0
#XS Ineff= 2 , 0
       06149.834                       0
Bank Sta=1038.888,12763.33
Exp/Cntr=0.3,0.1

Type RM Length L Ch R = 1 ,9084.037,960.607300,960.607300,960.607300
XS GIS Cut Line= 6
488837.285659443723038.085976122486840.093647882719420.156962978
485951.828997987717543.126278332484582.027745188  714316.4863651
 484161.23899183713533.111095959483651.773525824712786.896438143
#Sta/Elev= 30
1062.94346.845371205.86544.480011333.59349.179091438.09737.830152201.44525.45522
2236.10230.128052247.65426.553643268.38519.583434290.96718.637984313.6087.845889
4347.569  18.0646502.05211.317096612.0985.8437057489.52310.404179992.0891.768887
   100798.17419410122.643.55276810703.19 3.90198 11523.532.4404311689.7140.36525
11795.4749.8427111813.6156.6035111832.6549.48001 11924.872.7447512142.23  97.105
12239.36116.454612281.14115.115412448.9777.6884112517.7684.4801612572.47102.1478
#Mann= 3 , 0 , 0
1062.943  0.0494       01062.943  0.0494       012572.47  0.0494       0
#XS Ineff= 2 , 0
       06452.224                       0
Bank Sta=1062.943,12572.47
Exp/Cntr=0.3,0.1

Type RM Length L Ch R = 1 ,8123.429,960.607300,960.607300,960.607300
XS GIS Cut Line= 6
487036.504640294717414.440655176 486428.00884364716122.428452461
485544.824319409714133.542247172485061.561923953713337.868260898
484764.268599583712933.773056705484516.820171819 712636.99665833
#Sta/Elev= 30
6980.49763.432736991.00859.459997024.40964.38821 7113.4866.464187235.58777.95867
7313.20276.638227412.99365.48521 7534.96 46.85837590.35245.300517678.67833.86986
7744.92233.377057844.28920.862438104.4046.9289398866.8323.4940959697.9636.991844
9730.5714.7846649967.9816.01568810011.061.47501810075.6710.0793810129.823.169107
 10663.53.10509310997.485.04589511163.8611.3607411268.5718.8018211790.8343.21892
12080.9553.84177 12239.1 75.649512328.5381.1610612368.09  91.64212405.02105.5085
#Mann= 3 , 0 , 0
6980.497  0.0504       06980.497  0.0504       012405.02  0.0504       0
#XS Ineff= 2 , 0
       0                               0
Bank Sta=6980.497,12405.02
Exp/Cntr=0.3,0.1

Type RM Length L Ch R = 1 ,7162.822,960.607300,960.607300,960.607300
XS GIS Cut Line= 6
488110.484887846716928.942735042487152.819334139715054.327470098
486811.569671045 714462.24199422485916.521666263713262.282280171
485580.422630922712854.427027114 485255.19493904712509.047240181
#Sta/Elev= 30
6853.719122.48776994.52694.385157028.60894.719667051.329100.08827108.132104.8767
7244.591104.64617346.16293.074947492.74569.015237649.93452.796218013.80330.48662
8130.92515.461038576.8517.5649659383.61810.677239858.1276.8889129919.54613.23797
9980.9652.12677710018.171.42821710030.664.97415110069.426.63396310406.743.179854
11022.675.90235311149.2116.9196711549.0234.9978311614.9540.8027711707.9860.00744
11815.46 93.704411855.69102.736611952.52102.424712049.6595.7875512142.96117.3382
#Mann= 3 , 0 , 0
6853.719   0.069       06853.719   0.069       012142.96   0.069       0
#XS Ineff= 2 , 0
       08434.242                       0
Bank Sta=6853.719,12142.96
Exp/Cntr=0.3,0.1

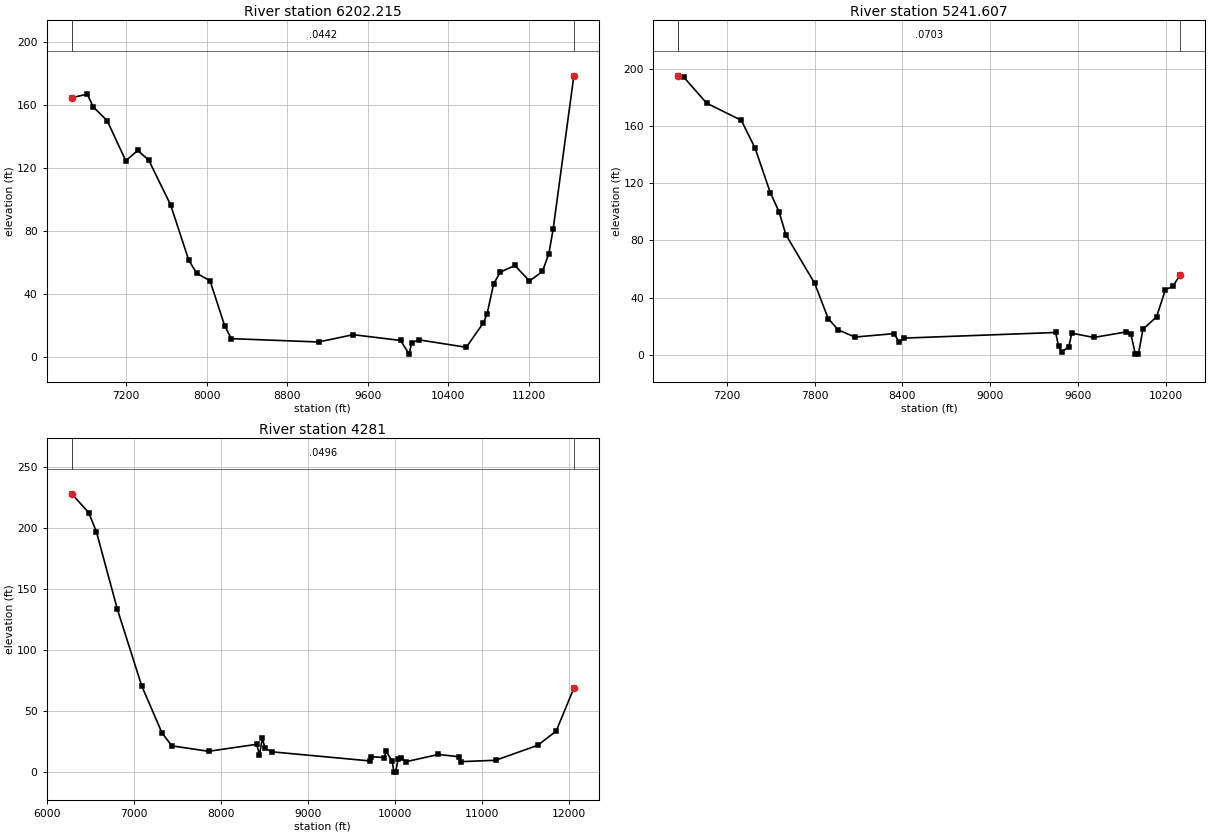
Type RM Length L Ch R = 1 ,6202.215,960.607300,960.607300,960.607300
XS GIS Cut Line= 6
488844.203647841 716597.26165175488483.541094847715974.891481092
488128.346761631715282.488845546487485.131809003713760.994913656
486796.166063633712759.950154223486368.365839314712316.151199698
#Sta/Elev= 30
6662.229 164.6166816.575166.87716874.876158.73917013.808149.97927198.258124.5149
7317.042131.06917426.977124.83967642.53896.548147822.72161.424347901.13453.00218
8034.68748.202998179.20719.704728245.42511.389799112.3479.2674859455.27313.90834
9926.01610.2458410011.231.54748710035.678.783798   1010910.6174910578.355.908708
10748.2621.49276 10784.927.2331110849.2546.1647210915.1453.6577611060.7957.91708
11205.3148.0272711333.3854.0972111397.6765.35648 11440.681.1518811645.74178.5227
#Mann= 3 , 0 , 0
6662.229  0.0442       06662.229  0.0442       011645.74  0.0442       0
#XS Ineff= 2 , 0
       08889.359                       0
Bank Sta=6662.229,11645.74
Exp/Cntr=0.3,0.1

Type RM Length L Ch R = 1 ,5241.607,960.607300,960.607300,960.607300
XS GIS Cut Line= 6
489353.820151665716366.887067826488751.116101031715379.644639485
488350.311151543714483.831067645488259.749296244714114.278536463
488239.314368342713871.306659344488341.998379369713213.446895142
#Sta/Elev= 30
6867.779195.1142 6906.16194.15967061.502176.03597298.965164.02587393.211144.5832
7497.364113.41727557.326100.0213 7603.8884.043657800.877 50.02097892.96225.46997
7961.55317.51241 8075.4112.501328343.02114.885338378.6398.995115 8412.0111.77226
9448.179 15.69549468.3476.2356649488.4831.9582219538.6355.7637489558.69515.22256
 9708.7812.222819931.17916.082979962.29314.746019993.446 0.6560210014.280.568286
10045.5517.9990410138.0726.5605410198.9545.5867710249.27 47.930310300.8655.93152
#Mann= 3 , 0 , 0
6867.779  0.0703       06867.779  0.0703       010300.86  0.0703       0
#XS Ineff= 2 , 0
       09420.256                       0
Bank Sta=6867.779,10300.86
Exp/Cntr=0.3,0.1

Type RM Length L Ch R = 1 ,    4281,0.000000,0.000000,0.000000
XS GIS Cut Line= 6
492037.397275236715256.270175274489658.737949673713410.079636066
489263.848177446713223.246334453488622.126483325713104.532221333
487852.196367992712299.238813875487408.159166742711992.459038469
#Sta/Elev= 30
 6287.05227.66976480.301212.40856569.421196.84366811.319133.25727091.411 70.5907
7323.16432.427177436.61521.719397859.24517.267428412.10922.964128444.47314.32291
8476.838 27.74298509.20319.677448587.70816.825119714.9729.3803419725.45612.84987
9878.99412.152989899.13217.260769969.2029.3324959989.2050.24129910009.210.537757
10039.2111.2390910069.2211.7204510129.268.763552   1049914.6743710731.8112.89227
10758.168.81162111157.88 9.9195811642.3122.1619711854.4533.8360612057.0868.86023
#Mann= 3 , 0 , 0
 6287.05  0.0496       0 6287.05  0.0496       012057.08  0.0496       0
#XS Ineff= 2 , 0
       08770.808        10289.03       0
Bank Sta=6287.05,12057.08
Exp/Cntr=0.3,0.1